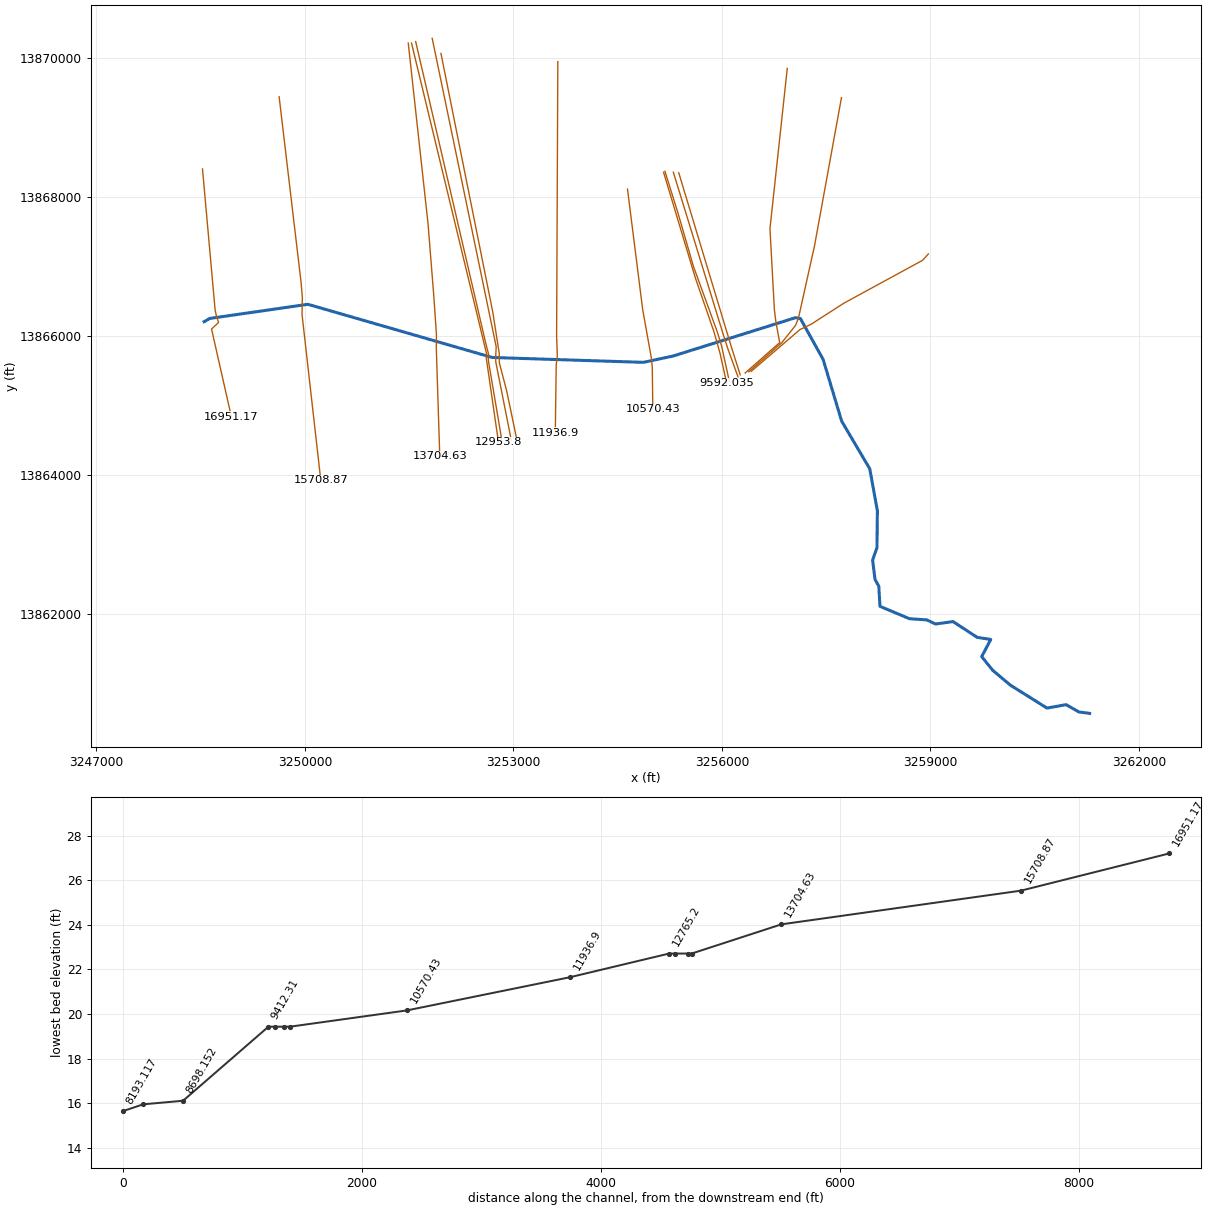
--- Q114-00-00.prj (project) ---

Proj Title=Q114-00-00
Current Plan=p02
Default Exp/Contr=0.3,0.1
English Units
Geom File=g01
Flow File=f02
Flow File=f01
Plan File=p02
Plan File=p01
Y Axis Title=Elevation
X Axis Title(PF)=Main Channel Distance
X Axis Title(XS)=Station
BEGIN DESCRIPTION:
Cedar Bayou Watershed
McGee Gully
HCFCD Unit Q114-00-00
(Flood Hazard) Model
10, 2, 1, 0.2% Event
Filename q1140000.prj
Prepared by:  FTN Associates Ltd.   DATE:  May 2003
Reviewed by:     DATE:
STATUS (Final)
Starting slope of 0.00169 for normal depth based on average minimum invert slope between RS 4108 and 155, assumed to be representative of typical channel slope.
END DESCRIPTION:
DSS File=dss
DSS Export Rating Curves= 0
DSS Export Rating Curve Sorted= 0
DSS Export Volume Flow Curves= 0
DXF OffsetX= 0
DXF OffsetY= 0
DXF ScaleX= 1
DXF ScaleY= 10

--- Q114-00-00.p02 (plan) ---

Plan Title=FEMA Effective Floodway 2016
Program Version=4.10
Short Identifier=Eff+LOMR_FW
Geom File=g01
Flow File=f02
Subcritical Flow
K Sum by GR= 0
Std Step Tol= 0.01
Critical Tol= 0.01
Num of Std Step Trials= 20
Max Error Tol= 0.3
Flow Tol Ratio= 0.001
Split Flow NTrial= 30
Split Flow Tol= 0.02
Split Flow Ratio= 0.02
Log Output Level= 0
Friction Slope Method= 1
Unsteady Friction Slope Method= 2
Unsteady Bridges Friction Slope Method= 1
Parabolic Critical Depth
Global Vel Dist= 0 , 0 , 0
Global Log Level= 0
CheckData=True
Encroach Param=-1 ,0,0, 2
Encroach River=Q114-00-00
Encroach Reach=Q114-00-00_0002
Encroach Node=16951.17
       1    1630    2000
Encroach Node=15708.87
       1    1575    1925
Encroach Node=13704.63
       1    2800    3300
Encroach Node=12953.8
       1 4183.46 4294.88
Encroach Node=12923.67
       1 4210.99 4322.41
Encroach Node=12869.84
       1    4220    4320
Encroach Node=12816.02
       1 4223.94 4315.36
Encroach Node=12765.2
       1 4409.47 4500.89
Encroach Node=11936.9
       1 2969.83 3048.73
Encroach Node=10570.43
       1 1561.49    1675
Encroach Node=9592.035
       1 2499.57 2632.72
Encroach Node=9543.269
       1 2512.59 2641.51
Encroach Node=9506.650
       1    2513    2645
Encroach Node=9470.032
       1    2513 2648.11
Encroach Node=9412.31
       1 2419.96 2559.39
Encroach Node=8698.152
       1  1314.5 1385.17
Encroach Node=8364.514
       1  715.83  786.18
Encroach Node=8193.117
       1    1787    1870
Encroach Node=8009.615
       1 1799.61  1855.3
Encroach Node=7826.113
       1 1799.61 1850.76
Encroach Node=7675.639
       1 1794.74  1887.6
Encroach Node=6825.093
       1     382     444
Encroach Node=6803.659
       1  381.11   442.6
Encroach Node=6779.073
       1  381.11   442.6
Encroach Node=6754.488
       1  382.31  427.73
Encroach Node=6728.82
       1  378.74  424.16
Encroach Node=6146.156
       1  111.97     188
Encroach Node=6125.334
       1  117.25  193.28
Encroach Node=6111.109
       1     117  193.28
Encroach Node=6096.884
       1     117  193.03
Encroach Node=6076.856
       1  167.74  243.77
Encroach Node=5319.128
       1  153.11  213.11
Encroach Node=4224.209
       1  158.92  243.43
Encroach Node=4204.437
       1  167.53  252.04
Encroach Node=4153.829
       1  150.69  252.04
Encroach Node=4103.221
       1  150.69   235.2
Encroach Node=4075.117
       1  156.44  240.95
Encroach Node=3754.204
       1  114.84  224.84
Encroach Node=2465.609
       1     235     300
Encroach Node=1571.249
       1     190     285
Encroach Node=1503.444
       1  165.65  311.04
Encroach Node=1465.252
       1      67     401
Encroach Node=1427.06
       1   171.2     308
Encroach Node=1365.134
       1     235     330
Encroach Node=618.632
       1     320     460
Encroach Node=567.508
       1     320     487
Encroach Node=555.119
       1     320     487
Encroach Node=542.73
       1     320     487
Encroach Node=490.831
       1     286     425
Encroach Node=155.909
       1     576   757.7
BEGIN DESCRIPTION:
FEMA Effective Multi-Profile June 2007 + LOMR 16-06-0437P + LOMR 18-06-2955P
END DESCRIPTION:
Computation Interval=1HOUR
Output Interval=1HOUR
Run HTab= 0
Run UNet= 0
Run PostProcess= 0
Run WQNet= 0
UNET Theta= 1
UNET Theta Warmup= 1
UNET ZTol= 0.02
UNET ZSATol= 0.1
UNET MxIter= 20
UNET MaxInSteps= 20
UNET DtIC= 0
UNET DtMin= 0
UNET MaxCRTS= 20
UNET WFStab= 2
UNET SFStab= 1
UNET WFX= 1
UNET SFX= 1
UNET DSS MLevel= 4
UNET DZMax Abort= 100
UNET Convert EG Bridges=-1
UNET Use Existing IB Tables=-1
UNET Froude Reduction=False
UNET Froude Limit= 1
UNET Froude Power= 10
UNET Time Slicing=0,0, 5
UNET Junction Losses=0
Instantaneous Interval=1HOUR
Write IC File= 0
Write IC File at Sim End=0
Echo Input=False
Echo Parameters=False
Echo Output=False
Write Detailed= 0
WQ AD Non Conservative
WQ ULTIMATE=-1
WQ Max Comp Step=1HOUR
WQ Output Interval=15MIN
WQ Output Selected Increments= 0
WQ Output face flow=0
WQ Output face velocity=0
WQ Output face area=0
WQ Output face dispersion=0
WQ Output cell volume=0
WQ Output cell surface area=0
WQ Output cell continuity=0
WQ Output cumulative cell continuity=0
WQ Output face conc=0
WQ Output face dconc_dx=0
WQ Output face courant=0
WQ Output face peclet=0
WQ Output face adv mass=0
WQ Output face disp mass=0
WQ Output cell mass=0
WQ Output cell source sink temp=0
WQ Output cell source sink nsm=0
WQ Output MaxMinRange=-1
WQ Daily Max Min Mean=-1
WQ Daily Range=0
WQ Daily Time=0
WQ Create Restart=0
WQ Fixed Restart=0
WQ System Summary=0
WQ Use Fixed Temperature=0
Sorting and Armoring Iterations= 10
XS Update Threshold= 0.02
Hydraulics Update Threshold= 0.02
Energy Slope Method= 1
Volume Change Method= 0
XS Weighting Method= 0
Number of US Weighted Cross Sections= 1
Number of DS Weighted Cross Sections= 1
Upstream XS Weight=0.25
Main XS Weight=0.5
Downstream XS Weight=0.25
Number of DS XS's Weighted with US Boundary= 1
Upstream Boundary Weight= 1
Weight of XSs Associated with US Boundary= 0
Number of US XS's Weighted with DS Boundary= 1
Downstream Boundary Weight= 0.5
Weight of XSs Associated with DS Boundary= 0.5
Sediment Output Level= 4
Mass or Volume Output= 0
Output Increment Type= 1
Profile and TS Output Increment= 10
XS Output Flag= 0
XS Output Increment= 10
Disregard all LS=0
Disregard all Conn=0
Disregard all Breaches=0
Disregard all Pumps=0

--- Q114-00-00.p01 (plan) ---

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Plan Title=FEMA Effective Multi-Profile 2016
Short Identifier=Eff+LOMR_MP
Geom File=g01
Flow File=f01
DSS File=dss

--- Q114-00-00.f02 (steady flow) ---

Flow Title=FEMA Effective Floodway
Program Version=4.10
Number of Profiles= 2
Profile Names=1PCT_100yr,1PCTFloodway_100yrFW
River Rch & RM=Q114-00-00,Q114-00-00_0002 ,16951.17
     450     450
River Rch & RM=Q114-00-00,Q114-00-00_0002 ,15708.87
     450     450
River Rch & RM=Q114-00-00,Q114-00-00_0002 ,13704.63
     816     816
River Rch & RM=Q114-00-00,Q114-00-00_0002 ,12953.8
   953.1   953.1
River Rch & RM=Q114-00-00,Q114-00-00_0002 ,12765.2
   987.5   987.5
River Rch & RM=Q114-00-00,Q114-00-00_0002 ,11936.9
   909.8   909.8
River Rch & RM=Q114-00-00,Q114-00-00_0002 ,10570.43
   883.9   883.9
River Rch & RM=Q114-00-00,Q114-00-00_0002 ,9592.035
   865.4   865.4
River Rch & RM=Q114-00-00,Q114-00-00_0002 ,9412.31
     862     862
River Rch & RM=Q114-00-00,Q114-00-00_0002 ,8698.152
  1024.2  1024.2
River Rch & RM=Q114-00-00,Q114-00-00_0002 ,8364.514
    1100    1100
River Rch & RM=Q114-00-00,Q114-00-00_0002 ,8193.117
  1138.9  1138.9
River Rch & RM=Q114-00-00,Q114-00-00_0002 ,7826.113
  1222.3  1222.3
River Rch & RM=Q114-00-00,Q114-00-00_0002 ,7675.639
  1240.5  1240.5
River Rch & RM=Q114-00-00,Q114-00-00_0002 ,6825.093
  1343.4  1343.4
River Rch & RM=Q114-00-00,Q114-00-00_0002 ,6076.856
  1433.8  1433.8
River Rch & RM=Q114-00-00,Q114-00-00_0002 ,5319.128
  1525.5  1525.5
River Rch & RM=Q114-00-00,Q114-00-00_0002 ,4224.209
  1657.9  1657.9
River Rch & RM=Q114-00-00,Q114-00-00_0002 ,3754.204
  1714.7  1714.7
River Rch & RM=Q114-00-00,Q114-00-00_0002 ,2465.609
  1870.6  1870.6
River Rch & RM=Q114-00-00,Q114-00-00_0002 ,1503.444
  1986.9  1986.9
River Rch & RM=Q114-00-00,Q114-00-00_0002 ,1427.06
  1996.2  1996.2
River Rch & RM=Q114-00-00,Q114-00-00_0002 ,490.831
  2109.4  2109.4
Boundary for River Rch & Prof#=Q114-00-00,Q114-00-00_0002 , 1
Up Type= 0
Dn Type= 3
Dn Slope=0.00169
Boundary for River Rch & Prof#=Q114-00-00,Q114-00-00_0002 , 2
Up Type= 0
Dn Type= 3
Dn Slope=0.00169
DSS Import GetInterval= 0
DSS Import GetPeak= 0
DSS Import FillOption= 0

--- Q114-00-00.f01 (steady flow) ---

Flow Title=FEMA Effective Multi-Profile 2016
Program Version=4.10
Number of Profiles= 4
Profile Names=10PCT_10yr,2PCT_50yr,1PCT_100yr,0.2PCT_500yr
River Rch & RM=Q114-00-00,Q114-00-00_0002 ,16951.17
   252.5   382.4     450   647.4
River Rch & RM=Q114-00-00,Q114-00-00_0002 ,15708.87
   252.5   382.4     450   647.4
River Rch & RM=Q114-00-00,Q114-00-00_0002 ,13704.63
   466.9   693.5     816  1158.3
River Rch & RM=Q114-00-00,Q114-00-00_0002 ,12953.8
   547.2     810   953.1  1349.6
River Rch & RM=Q114-00-00,Q114-00-00_0002 ,12765.2
   567.4   839.3   987.5  1397.7
River Rch & RM=Q114-00-00,Q114-00-00_0002 ,11936.9
   319.5   730.8   909.8  1397.7
River Rch & RM=Q114-00-00,Q114-00-00_0002 ,10570.43
   419.9   712.6   883.9  1346.7
River Rch & RM=Q114-00-00,Q114-00-00_0002 ,9592.035
   491.8   699.5   865.4  1310.1
River Rch & RM=Q114-00-00,Q114-00-00_0002 ,9412.31
     505   697.1     862  1303.4
River Rch & RM=Q114-00-00,Q114-00-00_0002 ,8698.152
   622.2   865.8  1024.2  1467.8
River Rch & RM=Q114-00-00,Q114-00-00_0002 ,8364.514
     677   944.6    1100  1544.6
River Rch & RM=Q114-00-00,Q114-00-00_0002 ,8193.117
   705.2   985.1  1138.9  1584.1
River Rch & RM=Q114-00-00,Q114-00-00_0002 ,7826.113
   765.4  1071.8  1222.3  1668.6
River Rch & RM=Q114-00-00,Q114-00-00_0002 ,7675.639
   775.5  1087.2  1240.5  1694.1
River Rch & RM=Q114-00-00,Q114-00-00_0002 ,6825.093
   832.8  1174.3  1343.4    1838
River Rch & RM=Q114-00-00,Q114-00-00_0002 ,6076.856
   883.1  1250.9  1433.8  1964.6
River Rch & RM=Q114-00-00,Q114-00-00_0002 ,5319.128
   934.1  1328.5  1525.5  2092.9
River Rch & RM=Q114-00-00,Q114-00-00_0002 ,4224.209
  1007.8  1440.6  1657.9  2278.2
River Rch & RM=Q114-00-00,Q114-00-00_0002 ,3754.204
  1039.5  1488.7  1714.7  2357.7
River Rch & RM=Q114-00-00,Q114-00-00_0002 ,2465.609
  1126.2  1620.7  1870.6  2575.8
River Rch & RM=Q114-00-00,Q114-00-00_0002 ,1503.444
  1190.9  1719.2  1986.9  2738.6
River Rch & RM=Q114-00-00,Q114-00-00_0002 ,1427.06
  1196.1    1727  1996.2  2751.6
River Rch & RM=Q114-00-00,Q114-00-00_0002 ,490.831
  1259.1  1822.9  2109.4    2910
Boundary for River Rch & Prof#=Q114-00-00,Q114-00-00_0002 , 1
Up Type= 0
Dn Type= 3
Dn Slope=0.00169
Boundary for River Rch & Prof#=Q114-00-00,Q114-00-00_0002 , 2
Up Type= 0
Dn Type= 3
Dn Slope=0.00169
Boundary for River Rch & Prof#=Q114-00-00,Q114-00-00_0002 , 3
Up Type= 0
Dn Type= 3
Dn Slope=0.00169
Boundary for River Rch & Prof#=Q114-00-00,Q114-00-00_0002 , 4
Up Type= 0
Dn Type= 3
Dn Slope=0.00169
DSS Import GetInterval= 0
DSS Import GetPeak= 0
DSS Import FillOption= 0

--- Q114-00-00.g01 (geometry) ---

Geom Title=Q114-00-00
Program Version=4.10

River Reach=Q114-00-00      ,Q114-00-00_0002
Reach XY= 30
      3248549.84    13866204.249     3248631.527    13866250.896
     3250042.316    13866453.872     3252694.821    13865688.725
     3254870.441    13865618.803     3255300.129    13865710.816
     3257060.759    13866262.368     3257128.891    13866248.174
     3257455.358    13865660.535     3257722.208    13864771.979
     3258126.517    13864086.685     3258236.078    13863482.986
     3258229.816    13862951.268     3258167.316    13862773.316
     3258201.972    13862495.232      3258255.91    13862398.711
     3258273.219    13862108.386      3258696.83    13861930.435
     3258947.698    13861913.073      3259071.83    13861854.046
     3259324.434    13861888.768     3259671.656    13861662.205
     3259866.969    13861631.823     3259736.761    13861384.428
     3259893.879    13861189.115     3260149.955    13860973.837
     3260676.583    13860644.117     3260950.658    13860693.921
     3261135.362    13860588.497     3261289.281     13860568.24

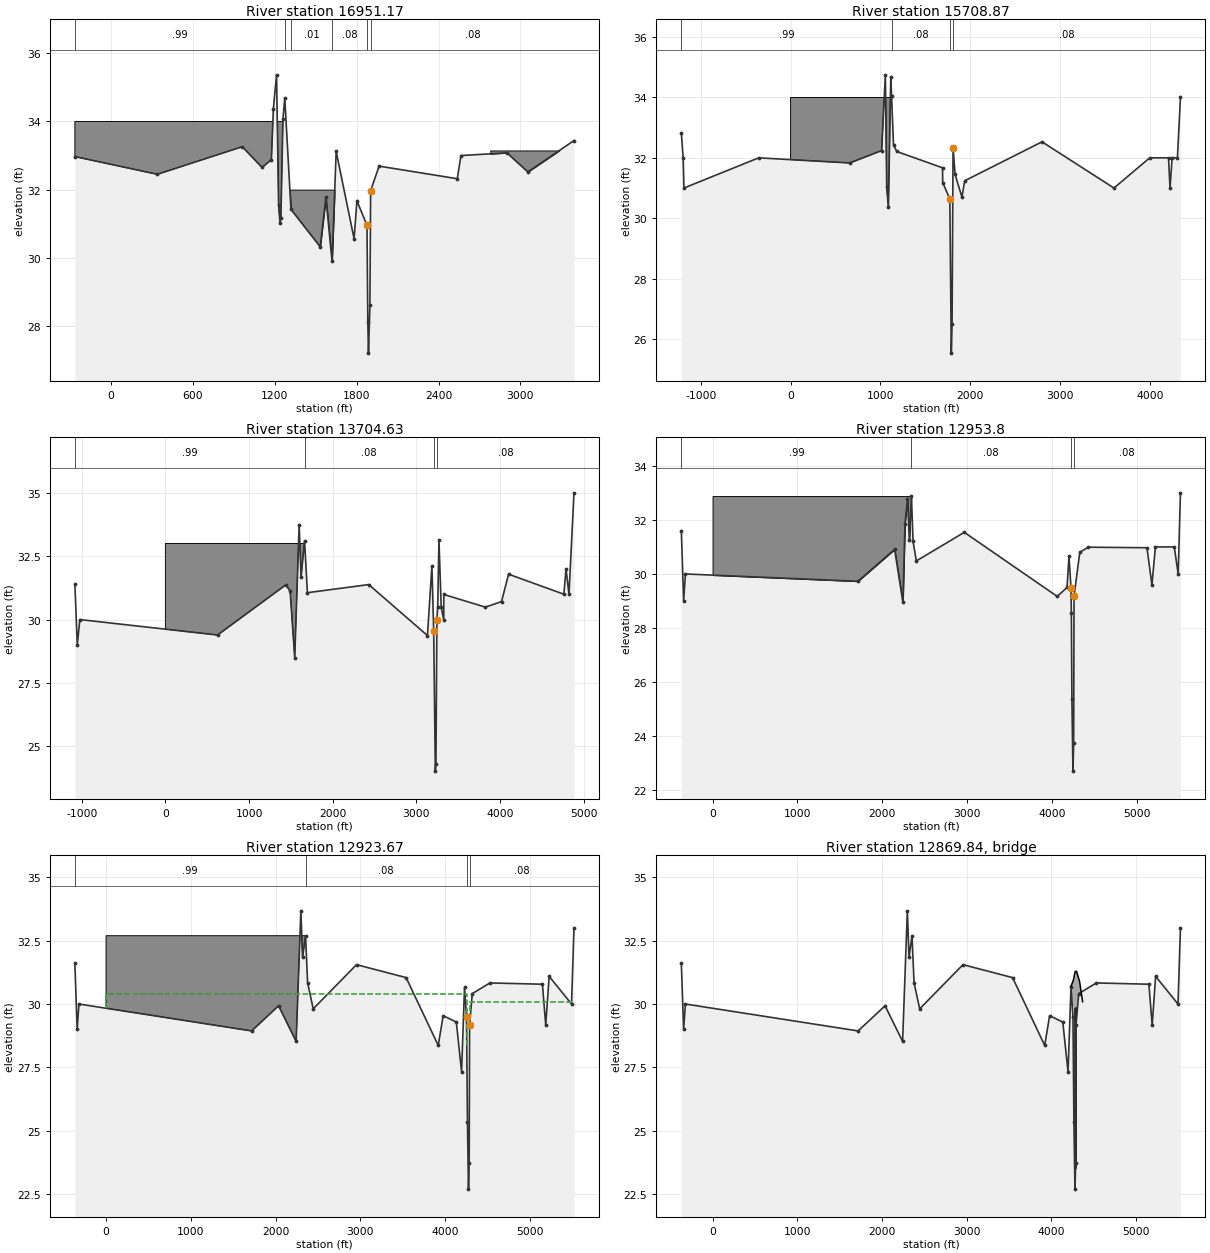
Type RM Length L Ch R = 1 ,16951.17,1309.2,1242.29,1318.27
BEGIN DESCRIPTION:
435v2
Bank Station offset =      3113
Block is pond and watershed divides
Overbank reachlengths > channel distance due to cross section orientation.
Manually extended LOB.
END DESCRIPTION:
XS GIS Cut Line= 6
 3248525.712120613868401.5175722     3248707.348    13866370.496
     3248727.133    13866280.073     3248757.412    13866192.731
     3248655.804    13866098.458     3248941.106    13864836.416
#Sta/Elev= 30
    -264   32.97  340.22   32.45  962.67   33.26 1107.35   32.65 1175.72   32.88
 1190.34   34.38 1213.58   35.37 1228.64   31.56 1238.52   31.03 1245.22   31.16
 1260.37   34.07 1273.82   34.69    1319   31.42 1533.48   30.32 1575.01   31.77
 1620.19   29.89 1650.31   33.12 1781.45   30.56 1802.62   31.67 1876.12   30.95
 1882.11   28.12 1887.07    27.2 1897.59   28.62 1902.81   31.97 1964.86   32.69
 2537.46   32.32 2564.52      33  2901.4   33.08  3054.5   32.52 3392.63   33.44
#Mann= 6 ,-1 , 0
    -264     .99       0 1273.82     .08       0    1319     .01       0
 1620.19     .08       0 1876.12     .04       0 1902.81     .08       0
#Block Obstruct= 3 ,-1
 1278.59 1638.09      32    -264    1274      34    2779    3300   33.15
Bank Sta=1876.12,1902.81
XS Rating Curve= 0 ,0
Exp/Cntr=0.3,0.1

Type RM Length L Ch R = 1 ,15708.87,1997.22,2004.25,2009.52
BEGIN DESCRIPTION:
435v3
Bank Station offset =      3212
LOB manually extended to boundary of watershed.
ROB block added to area not effective flow
0.99 used on far LOB because of lateral drainage channels that connects to stream.
END DESCRIPTION:
XS GIS Cut Line= 6
 3249628.295558213869439.5917012     3249771.065    13868232.002
      3249943.56    13866772.984     3249962.822    13866546.437
     3249957.935     13866305.81 3250227.773987313863919.8597585
#Sta/Elev= 30
   -1216   32.83   -1196      32   -1187      31    -355      32   658.7   31.83
 1013.13   32.24 1054.48   34.75 1069.58   31.03 1088.33   30.36  1114.9   34.69
 1123.19   34.06 1145.11   32.43 1181.33   32.21 1690.69   31.67 1692.93   31.18
 1771.64   30.64 1788.31   25.53 1796.78   26.49 1807.75   32.34 1830.58   31.45
 1906.52    30.7 1937.22   31.24 2797.75   32.53 3598.38      31 3996.38      32
 4205.38      32 4222.38      31 4245.38      32 4304.38      32 4338.38      34
#Mann= 4 ,-1 , 0
   -1216     .99       0 1123.19     .08       0 1771.64     .04       0
 1807.75     .08       0
#Block Obstruct= 2 , 0
       0    1115      34    2797       0   33.53
Bank Sta=1771.64,1807.75
XS Rating Curve= 0 ,0
Exp/Cntr=0.3,0.1

Type RM Length L Ch R = 1 ,13704.63,834.37,750.82,728.99
BEGIN DESCRIPTION:
435v4
Bank Station offset =      1774
LOB manually extended to boundary of watershed.
0.99 used on far LOB because of lateral drainage channels that connects to stream.
END DESCRIPTION:
XS GIS Cut Line= 6
 3251485.989477213870213.1637338     3251770.798    13867613.457
     3251855.377    13866550.178     3251891.759    13866017.603
     3251889.614    13865823.525 3251939.571134713864268.1350086
#Sta/Elev= 30
   -1082    31.4   -1053      29   -1023      30  623.49   29.39 1440.35   31.37
 1491.22   31.12 1545.93    28.5 1598.96   33.75 1621.56   31.67 1663.21   33.11
 1697.57   31.06 2430.62   31.38 3132.26   29.37 3185.63   32.11 3207.21   29.55
 3226.28   24.02 3234.03   24.32 3245.11   29.99 3254.81   30.49 3269.81   33.13
 3297.21   30.48 3327.54   29.98  3327.8   30.99 3824.74   30.49 4018.05   30.71
 4101.79   31.79    4763      31    4789      32    4824      31    4884      35
#Mann= 4 ,-1 , 0
   -1082     .99       0 1663.21     .08       0 3207.21     .04       0
 3245.11     .08       0
#Block Obstruct= 2 , 0
       0    1662      33    4100       0    32.8
Bank Sta=3207.21,3245.11
XS Rating Curve= 0 ,0
Exp/Cntr=0.3,0.1

Type RM Length L Ch R = 1 ,12953.8 ,39.39,30.13,21.61
BEGIN DESCRIPTION:
Copy of 435s2d.  XS 4/4.
IGNORE HUMP AT LOB.  ISLAND THAT WATER CAN FLOW AROUND.
Bank Station offset =       750
LOB manually extended to boundary of watershed.
0.99 used on far LOB because of lateral drainage channels that connects to stream.
Inverts were not adjusted at s2 because negative slope.
END DESCRIPTION:
XS GIS Cut Line= 6
 3251532.885533613870212.5974927     3251619.029    13869854.822
 3252614.569063313865735.1373714 3252607.967560213865683.4570332
     3252621.497    13865592.742 3252784.354182713864466.6318944
#Sta/Elev= 30
    -368    31.6    -341      29    -320      301714.109   29.732146.802   30.91
 2244.96   28.95 2269.45   31.86 2298.88   32.77  2320.7   31.25 2345.16   32.88
 2364.98   31.21 2402.64   30.48 2968.99   31.54 4064.54   29.174180.582    29.5
 4203.46   30.664226.931   29.49 4231.64   28.564237.878   25.37 4250.27   22.71
 4258.53   23.75 4263.16   29.18 4330.75    30.84432.081   30.99 5123.39   30.97
 5181.35   29.59 5222.37      31    5445      31    5491      30    5518      33
#Mann= 4 ,-1 , 0
    -368     .99       0 2345.16     .08       04226.931     .04       0
 4263.16     .08       0
#Block Obstruct= 2 , 0
       0    2345   32.885121.001       0   31.99
Bank Sta=4226.931,4263.16
XS Rating Curve= 0 ,0
Exp/Cntr=0.5,0.3

Type RM Length L Ch R = 1 ,12923.67,125.27,107.65,104.47
BEGIN DESCRIPTION:
Copy of 435s2d.  XS 3/4.
IGNORE HUMP AT near LOB.  ISLAND THAT WATER CAN FLOW AROUND.
Bank Station offset =       722
LOB manually extended to boundary of watershed.
Blocked far LOB due to shallow water.  Blocked at ROB based on downstream high ground, contraction of 1:1.
Inverts were not adjusted at s2 because negative slope.
END DESCRIPTION:
XS GIS Cut Line= 6
 3251592.497586313870235.3389491      3252604.97    13865875.779
 3252642.483990413865733.8170708 3252637.957245513865675.1580008
     3252641.508    13865627.288 3252835.574880613864480.8095096
#Sta/Elev= 30
    -368    31.6    -341      29    -320      30 1718.35   28.94 2036.49   29.93
 2243.44   28.53 2299.48   33.67 2319.33   31.84 2354.68   32.69 2378.73   30.84
 2445.03   29.81 2956.46   31.55 3541.57   31.04 3920.71   28.37 3978.74   29.54
 4134.32   29.29 4196.09   27.33 4230.99   30.66 4254.46   29.49 4265.41   25.37
  4277.8   22.71 4286.06   23.75 4290.69   29.18 4322.41   30.41 4530.54   30.83
 5150.51   30.78 5189.23   29.17 5229.88   31.09    5494      30    5523      33
#Mann= 4 ,-1 , 0
    -368     .99       0 2354.68     .08       0 4254.46     .04       0
 4290.69     .08       0
#XS Ineff= 2 , 0
       0 4257.55   30.41 4297.06       0   30.09
Permanent Ineff=
       F       F
#Block Obstruct= 2 , 0
       0 2354.68   32.69    4635       0   32.09
Bank Sta=4254.46,4290.69
XS Rating Curve= 0 ,0
Exp/Cntr=0.5,0.3

Type RM Length L Ch R = 3 ,12869.84,,,
BEGIN DESCRIPTION:
435s2 - Foot Bridge
Several survey points were taken along the top of bridge and the adjacent path.  All these points were used in the deck/roadway data.
END DESCRIPTION:
Bridge Culvert--1,0,-1,-1, 0
Deck Dist Width WeirC Skew NumUp NumDn MinLoCord MaxHiCord MaxSubmerge Is_Ogee
46,15.8,2.6,0, 6, 6, , , 0.95, 0, 0,0,,
    4231 4259.36 4280.13 4296.51 4332.83  4368.2
    30.7   30.94   31.28   31.29   30.88   30.09
           29.88   29.88   29.88
 4223.92 4252.36 4273.13 4289.51 4326.83  4362.2
   30.67   30.94   31.28   31.29   30.88   30.09
           29.88   29.88   29.88
Pier Skew, UpSta & Num, DnSta & Num=  ,4271.5, 4 ,4264.5, 4 , 3 , 3 , 0 ,0,
       1       1     1.1     1.1
       0   28.78   28.78   29.88
       1       1     1.1     1.1
       0   28.78   28.78   29.88
Pier Skew, UpSta & Num, DnSta & Num=  ,4284.34, 4 ,4277.34, 4 , 3 , 3 , 0 ,0,
       1       1     1.1     1.1
       0   28.78   28.78   29.88
       1       1     1.1     1.1
       0   28.78   28.78   29.88
BR Coef=-1 , 0 , 0 ,, 0 ,,,0.8,0,,1,
WSPro=,,,, 1 ,,,, 0 ,,,, 0 ,,,,-1 ,-1 ,-1 , 0 , 0 , 0 , 0 , 0
BC Design=,, 0 ,, 0 ,,,,,,
BC HTab HWMax=33.8
BC Use User HTab Curves=0
BC User HTab FreeFlow(D)= 0

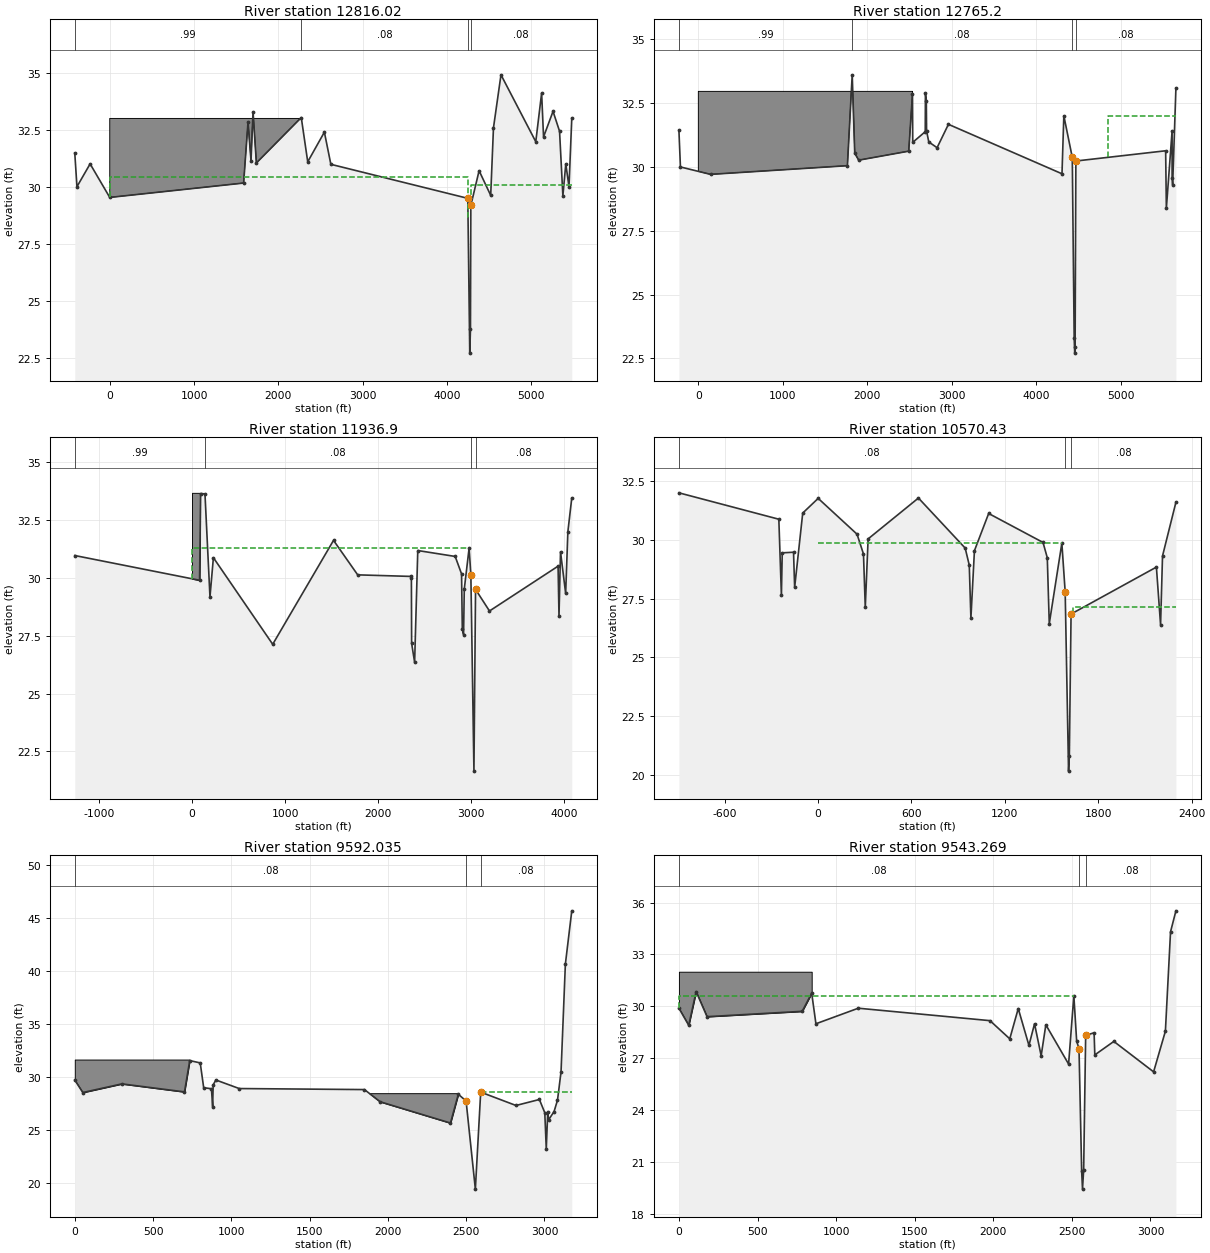
Type RM Length L Ch R = 1 ,12816.02,47.47,50.81,52.8
BEGIN DESCRIPTION:
Copy of 435s2d.  XS 2/4.
Bank Station offset =       729
LOB and ROB manually extended to boundary of watershed.
0.99 used on far LOB because of lateral drainage channels that connects to stream.
Inverts were not adjusted at s2 because negative slope.
END DESCRIPTION:
XS GIS Cut Line= 6
 3251830.530616213870280.7215973     3252751.332    13865844.383
     3252745.092    13865712.809     3252745.092    13865625.956
     3252950.239    13864590.428 3252967.899853613864501.2806649
#Sta/Elev= 30
    -415   31.48    -389      30    -233      31       0   29.53 1588.13   30.16
 1640.41   32.83 1675.72   31.14 1699.74   33.28 1739.56   31.04 2271.98   33.03
 2348.58   31.09 2546.13   32.39 2623.01   30.98 4247.41   29.49 4270.75   22.71
 4279.01   23.75 4283.64   29.18  4381.5    30.7 4519.13   29.62 4552.08   32.58
 4641.21    34.9    5054   31.97 5123.28    34.1 5146.08   32.18 5258.71    33.3
  5335.9   32.43 5375.45    29.6    5410      31    5448      30    5481      33
#Mann= 4 ,-1 , 0
    -415     .99       0 2271.98     .08       0 4247.41     .04       0
 4283.64     .08       0
#XS Ineff= 2 , 0
       0 4250.56   30.41 4290.07       0   30.09
Permanent Ineff=
       F       F
#Block Obstruct= 2 , 0
       0 2271.07   32.99    5282       0      33
Bank Sta=4247.41,4283.64
XS Rating Curve= 0 ,0
Exp/Cntr=0.5,0.3

Type RM Length L Ch R = 1 ,12765.2 ,878.61,828.3,842.06
BEGIN DESCRIPTION:
435s2d.  XS 1/4.
Bank Station offset =       543
LOB manually extended to boundary of watershed.
0.99 used on far LOB because of lateral drainage channels that connects to stream.
Block added in ROB due to the hill in the immediate upstream cross section
Inverts were not adjusted at s2 because negative slope.
END DESCRIPTION:
XS GIS Cut Line= 6
     3251956.547    13870063.071     3252701.094    13866348.406
     3252794.808    13865750.545     3252796.605    13865612.179
     3252903.837    13865200.542     3253045.808    13864518.362
#Sta/Elev= 30
    -230   31.44    -212      30   144.8   29.71 1764.93   30.05 1821.72  33.608
 1851.81  30.539 1898.51  30.266 2490.92  30.619 2535.23  32.852 2538.45  30.964
 2686.39  31.381 2688.48  32.895 2699.18  32.595 2702.13  31.413 2728.16   30.98
 2826.62  30.754 2960.86   31.67 4305.36  29.733 4327.21  32.005 4427.19  30.375
 4449.63  23.302 4456.28   22.71 4460.62  22.958 4469.75  30.233  5532.6  30.634
 5540.99   28.38 5609.15  31.418 5609.25   29.55 5615.37    29.3 5654.26   33.09
#Mann= 4 ,-1 , 0
    -230     .99       0 1821.72     .08       0 4427.19     .04       0
 4469.75     .08       0
#XS Ineff= 2 , 0
       0                 4845.96       0      32
Permanent Ineff=
       F       F
#Block Obstruct= 2 , 0
       0  2535.4   32.96               0
Bank Sta=4427.19,4469.75
XS Rating Curve= 0 ,0
Exp/Cntr=0.3,0.1

Type RM Length L Ch R = 1 ,11936.9 ,1301.79,1366.47,1384.77
BEGIN DESCRIPTION:
435v5
Bank Station offset =      1971
Extended ROB to boundary of watershed.
END DESCRIPTION:
XS GIS Cut Line= 6
 3253638.113056613869946.1155952     3253620.601    13865999.639
     3253630.837    13865714.397     3253615.062    13865585.192
      3253602.65    13864671.277  3253601.78224713864607.3829899
#Sta/Elev= 30
   -1260   30.97    80.9    29.9   92.26  33.647  138.97  33.634  192.69  29.182
  229.43  30.877   866.8  27.133 1520.16  31.625  1779.8  30.134 2348.87  30.067
 2356.81  29.985 2359.31   27.17 2391.52  26.358 2425.39  31.186 2827.37   30.93
 2895.64  30.177 2903.89  27.796 2917.29  27.552    2925  29.518 2977.15  31.296
 2995.81  30.114 3028.83   21.65 3046.14  29.505 3195.79  28.572 3932.76   30.51
 3942.66  28.346 3959.02  31.133 4014.32   29.33    4038      32    4080   33.46
#Mann= 4 ,-1 , 0
   -1260     .99       0  138.97     .08       0 2995.81     .04       0
 3046.14     .08       0
#XS Ineff= 2 , 0
       0 2977.15    31.3 3046.14       0    29.5
Permanent Ineff=
       F       F
#Block Obstruct= 2 , 0
       0   86.31   33.68               0
Bank Sta=2995.81,3046.14
XS Rating Curve= 0 ,0
Exp/Cntr=0.3,0.1

Type RM Length L Ch R = 1 ,10570.43,978.91,978.4,1040.67
BEGIN DESCRIPTION:
435v6
Bank Station offset =      3391
Tributary in ROB block added at tributary
Manually extended LOB.
END DESCRIPTION:
XS GIS Cut Line= 6
 3254640.458123213868111.7216596     3254752.157    13867225.735
     3254859.209    13866376.607     3254982.914    13865685.786
     3254996.587    13865561.944     3255005.224    13864945.647
#Sta/Elev= 30
    -893      32 -251.31  30.877 -234.82  27.635 -229.52  29.447 -156.97  29.473
 -149.78  27.976  -97.93  31.139    1.31  31.764  250.91   30.24  292.22  29.397
  303.76  27.126  322.03   30.04  645.14  31.779  945.37  29.648  971.48  28.925
  982.07  26.664  1004.7  29.537 1096.11  31.121 1445.13  29.889 1472.52   29.24
 1485.28  26.432 1566.12  29.858 1587.48  27.781 1609.07   20.16 1614.12   20.79
 1625.25  26.843 2173.26   28.84 2200.05  26.386 2212.57  29.316 2298.61    31.6
#Mann= 3 ,-1 , 0
    -893     .08       0 1587.48     .04       0 1625.25     .08       0
#XS Ineff= 2 , 0
       0 1566.12   29.86 1635.55       0   27.13
Permanent Ineff=
       F       F
Bank Sta=1587.48,1625.25
XS Rating Curve= 0 ,0
Exp/Cntr=0.3,0.1

Type RM Length L Ch R = 1 ,9592.035,46.93,48.77,49.69
BEGIN DESCRIPTION:
435s3u.  XS 4/4.
Bank Station offset =      2441
Added block on LOB based on ~1:1 contraction to d/s high ground and to close section
END DESCRIPTION:
XS GIS Cut Line= 5
     3255159.257    13868354.594     3255617.893    13866830.737
     3255881.849    13866067.075     3255972.161    13865748.328
     3256068.586    13865314.846
#Sta/Elev= 30
       0   29.71    51.3   28.53  300.82  29.345  700.88  28.589  734.42   31.54
  801.42  31.322  823.52  28.985  873.07  28.887  880.72  27.205  884.08  29.254
  901.35  29.712 1050.61  28.906 1850.49  28.809 1950.26  27.662 2399.79  25.656
  2449.9  28.365 2499.57  27.739 2558.87   19.43 2592.94  28.569 2818.38  27.311
 2967.86  27.875 3002.29  26.631  3011.8   23.22 3021.26  26.731 3026.75   25.96
 3061.62   26.74 3083.52   27.81 3106.14   30.48 3133.83   40.63 3174.74   45.65
#Mann= 3 ,-1 , 0
       0     .08       0 2499.57     .04       0 2592.94     .08       0
#XS Ineff= 2 , 0
       0 2449.88   28.36 2592.94       0   28.57
Permanent Ineff=
       F       F
#Block Obstruct= 2 ,-1
    1850 2449.76   28.47       0  731.63   31.64
Bank Sta=2499.57,2592.94
XS Rating Curve= 0 ,0
Exp/Cntr=0.5,0.3

Type RM Length L Ch R = 1 ,9543.269,71.72,73.24,77.89
BEGIN DESCRIPTION:
Copy of 435s3u. XS 3/4. No elevation adjustment per photos.
Bank Station offset =      2432
Moved ineff sta's to channel banks.
Block on Left edge where high ground will likely contain flows
END DESCRIPTION:
XS GIS Cut Line= 6
     3255179.135    13868367.959     3255371.466    13867751.512
     3255588.455    13867001.912      3255935.28    13866049.117
      3255994.75    13865852.049     3256105.239    13865347.944
#Sta/Elev= 30
       0   29.89   62.41    28.9  109.55   30.85  178.94    29.4  784.28   29.71
  844.83   30.76  871.67   28.99 1141.35   29.89 1979.17   29.17 2104.89   28.12
 2158.85   29.87 2226.83   27.74 2262.51   28.99 2304.61   27.14 2334.44   28.93
 2479.16   26.66 2512.59   30.62 2530.51   27.98 2545.41   27.56 2562.26   20.48
 2567.66   19.43 2575.06   20.56 2587.82   28.32 2641.51   28.47 2645.93   27.19
 2767.02   27.97 3019.99   26.21 3095.01   28.56 3127.78   34.31    3162   35.52
#Mann= 3 ,-1 , 0
       0     .08       0 2545.41     .04       0 2587.82     .08       0
#XS Ineff= 2 , 0
       0 2512.59   30.62 2587.82       0      27
Permanent Ineff=
       F       F
#Block Obstruct= 2 , 0
       0  844.73      32               0
Bank Sta=2545.41,2587.82
XS Rating Curve= 0 ,0
Exp/Cntr=0.5,0.3

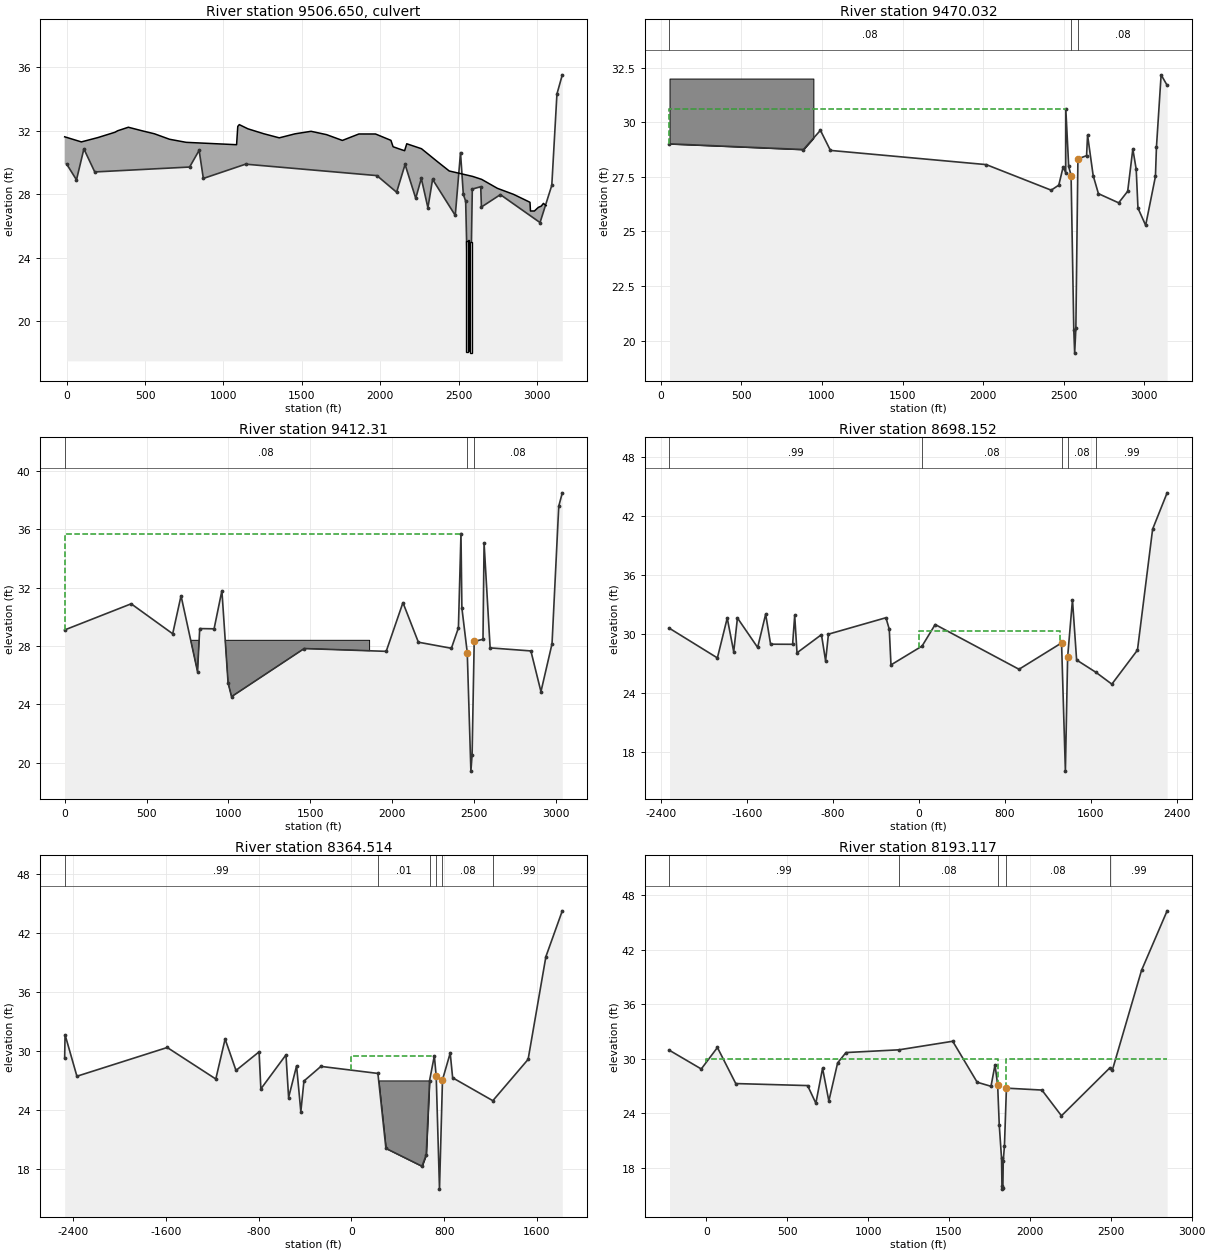
Type RM Length L Ch R = 2 ,9506.650,,,
BEGIN DESCRIPTION:
435s3 - N. Sjolander Rd. (3 Box Culverts)
Shift the centerline of 3 culverts (US: +1ft, DS: -1ft)
d/s section stationing adjusted by 54.19' to set enc stations at structure.
END DESCRIPTION:
Bridge Culvert--1,0,0,-1, 0
Deck Dist Width WeirC Skew NumUp NumDn MinLoCord MaxHiCord MaxSubmerge Is_Ogee
8.62,56,2.6,0, 41, 41, , , 0.95, 0, 0,0,,
     -13   93.48   199.2  307.93  325.15  393.21  484.17  559.93  655.48  761.79
  1083.8 1091.46 1101.01 1156.05 1255.91 1356.15 1457.01 1558.95 1657.98 1758.79
 1864.22 1970.44 2068.49 2082.45 2120.49  2155.9  2169.6 2263.51 2366.84 2440.54
 2590.26 2647.68 2747.85 2851.46 2955.85 2958.93 2983.96 3009.15 3027.81 3041.49
 3059.14
  31.615  31.294  31.568  31.903  31.996  32.218  31.986  31.805  31.462  31.267
  31.117  32.271  32.383  32.119  31.812   31.55  31.803  31.962  31.751  31.387
  31.793  31.792  31.392  30.989  30.855  30.739  31.176  30.865  30.038  29.462
  29.119  28.932  28.369  27.987  27.489  26.941  26.941  27.169   27.25  27.419
  27.278
                                               0       0       0       0       0
                                                                                
                                                                                
                                                                                
        
     -13   93.48   199.2  307.93  325.15  393.21  484.17  559.93  655.48  761.79
  1083.8 1091.46 1101.01 1156.05 1255.91 1356.15 1457.01 1558.95 1657.98 1758.79
 1864.22 1970.44 2068.49 2082.45 2120.49  2155.9  2169.6 2263.51 2366.84 2440.54
 2590.26 2647.68 2747.85 2851.46 2955.85 2958.93 2983.96 3009.15 3027.81 3041.49
 3059.14
  31.615  31.294  31.568  31.903  31.996  32.218  31.986  31.805  31.462  31.267
  31.117  32.271  32.383  32.119  31.812   31.55  31.803  31.962  31.751  31.387
  31.793  31.792  31.392  30.989  30.855  30.739  31.176  30.865  30.038  29.462
  29.119  28.932  28.369  27.987  27.489  26.941  26.941  27.169   27.25  27.419
  27.278
                                                       0       0       0       0
       0
                                                                                
                                                                                
        
BR Coef=-1 , 0 , 0 ,, 0 ,,,0.8,0,,1,
WSPro=,,,, 1 ,,,, 0 ,,,, 0 ,,,,-1 ,-1 ,-1 , 0 , 0 , 0 , 0 , 0
Culvert=2,7,10,66,0.015,0.5,1,10,1,18.049,2552.41,17.68,2557.32,Culvert #1  , 0 ,3.62
Culvert Bottom n=0.015
Culvert=2,7,10,66,0.015,0.5,1,10,1,18.108,2564.85,17.63,2570.46,Culvert #2  , 0 ,3.62
Culvert Bottom n=0.015
Culvert=2,7,10,66,0.015,0.5,1,10,1,17.985,2578.31,17.651,2582.48,Culvert #3  , 0 ,3.62
Culvert Bottom n=0.015
BC Design=,, 0 ,, 0 ,,,,,,
BC HTab HWMax=35.91
BC Use User HTab Curves=0
BC User HTab FreeFlow(D)= 0

Type RM Length L Ch R = 1 ,9470.032,70.14,57.72,75.43
BEGIN DESCRIPTION:
Copy of 435s3u.  XS 2/4. No elevation adjustment per photos.
Bank Station offset =      2486
Moved ineff sta's to channel banks.
Block on Left edge where ag levees would generally keep conveyance zone away from the far left overbank
END DESCRIPTION:
XS GIS Cut Line= 6
     3255299.945    13868354.716     3256011.934    13866040.646
     3256050.813    13865921.579     3256079.972    13865826.812
     3256186.889    13865530.359     3256230.628    13865411.292
#Sta/Elev= 30
   54.19   29.01  885.31   28.75  990.51   29.63 1052.66   28.71 2019.33   28.06
 2422.38   26.89 2469.46   27.12 2496.11   27.94 2512.55   27.69    2513   30.62
 2530.92   27.98 2545.82   27.56 2562.67   20.48 2568.07   19.43 2575.47   20.56
 2588.23   28.32 2641.92   28.47 2648.11   29.41 2682.82   27.56 2715.41   26.73
 2841.04   26.31 2896.99   26.84 2928.88   28.77 2949.79   27.85 2960.77   26.07
 3008.45   25.28 3069.24   27.52 3075.46   28.86 3104.47   32.17 3141.71   31.69
#Mann= 3 ,-1 , 0
   54.19     .08       0 2545.82     .04       0 2588.23     .08       0
#XS Ineff= 2 , 0
       0    2513   30.62 2588.23       0    26.8
Permanent Ineff=
       F       F
#Block Obstruct= 2 , 0
   54.19  946.94      32           54.19
Bank Sta=2545.82,2588.23
XS Rating Curve= 0 ,0
Exp/Cntr=0.5,0.3

Type RM Length L Ch R = 1 ,9412.31 ,751.9,714.16,713.13
BEGIN DESCRIPTION:
Copy of 435s3u. XS 1/4.
Bank Station offset =      2519
No elevation adjustment per photos (Spikes do exist).  Water can flow around.
Block on Left edge where ag levees would generally keep conveyance zone away from the far left overbank
END DESCRIPTION:
XS GIS Cut Line= 3
     3255378.031     13868346.38      3256135.94    13865837.531
     3256261.941    13865439.146
#Sta/Elev= 30
       0   29.11  406.02  30.901  659.58  28.848   710.6  31.451  811.24  26.255
  824.67  29.203  912.39  29.187  960.06  31.801  997.82  25.478 1019.01  24.535
 1462.78  27.834 1963.38  27.642  2065.6  30.981 2159.81  28.269 2361.36  27.852
 2404.29   29.25 2419.96   35.72 2425.46   30.62 2458.28   27.56 2480.53   19.43
 2487.93   20.56 2500.69   28.32 2554.38   28.47 2560.99   35.07 2597.95   27.88
 2846.87   27.67 2908.31   24.88 2975.92   28.16 3016.99   37.59 3038.67   38.51
#Mann= 3 ,-1 , 0
       0     .08       0 2458.28     .04       0 2500.69     .08       0
#XS Ineff= 2 , 0
       0 2419.96   35.72               0
Permanent Ineff=
       F       F
#Block Obstruct= 2 , 0
       0  1862.1    28.4               0
Bank Sta=2458.28,2500.69
XS Rating Curve= 0 ,0
Exp/Cntr=0.3,0.1

Type RM Length L Ch R = 1 ,8698.152,349.76,333.64,241.12
BEGIN DESCRIPTION:
435v7
Bank Station offset =      3636
No elevation adjustment per photos (Spikes do exist).  Water can flow around.
The assignment of the 0.99 "ineffective area" was determined based on the skew of the cross section indicating a wider flow area than is available in the direction of flow.
0.99 in Left overbank assigned based on the fact that much of the flow in this area is not effective. Flow should be contracting for the structure downstream (and not fully expanded from the structure upstream).
END DESCRIPTION:
XS GIS Cut Line= 6
     3256939.451    13869848.837      3256690.33    13867543.492
     3256754.115    13866373.378     3256775.839    13866199.591
     3256830.566     13865903.15     3256333.458     13865465.33
#Sta/Elev= 30
-2318.84   30.59 -1873.3   27.59-1781.71   31.63-1721.36   28.21-1686.77   31.64
-1498.79  28.652-1424.21  32.026-1378.41  28.982-1173.42   28.97-1154.05  31.899
-1132.56  28.108 -905.02   29.95 -866.51  27.283  -840.2  29.998 -305.29  31.664
 -274.22  30.506 -258.31  26.881   30.93  28.792  152.95  30.977  932.87  26.438
 1328.73   29.11 1364.28   16.11 1385.17   27.68 1430.14   33.48 1468.73   27.38
 1648.41   26.13  1796.6   24.93 2034.82   28.38 2175.92   40.65 2310.83   44.33
#Mann= 5 ,-1 , 0
-2318.84     .99       0   30.93     .08       0 1328.73     .04       0
 1385.17     .08       0 1648.41     .99       0
#XS Ineff= 2 , 0
       0  1314.5   30.32               0
Permanent Ineff=
       F       F
Bank Sta=1328.73,1385.17
XS Rating Curve= 0 ,0
Exp/Cntr=0.5,0.3

Type RM Length L Ch R = 1 ,8364.514,199.41,171.4,166.13
BEGIN DESCRIPTION:
Copy of 435s4u.  XS 4/4.  Adjusted elevations +0.31.  Combined structures 4, 5, and 6 into single structure.
Bank Station offset =      4240
Block in LOB is contained low area. 0.99 in LOB is area that is ineffective due to flow contracting for structure.  0.99 in ROB is I-10 embankment.
Manually extended LOB.
END DESCRIPTION:
XS GIS Cut Line= 6
     3257719.354    13869427.131     3257330.534    13867291.351
     3257100.857    13866257.841     3257058.581    13866150.744
     3256861.297    13865902.729     3256384.996    13865482.796
#Sta/Elev= 30
-2476.07    29.3-2472.73  31.646-2370.35  27.425-1590.49  30.347-1171.08  27.145
-1090.77  31.207-996.721  28.013-797.341  29.906-782.131  26.136-565.241    29.6
-542.491  25.262-473.701  28.476-436.851  23.814-410.151  26.939-263.531  28.426
  228.62  27.711  297.78  20.092  609.39  18.275  645.84  19.443  674.73  26.988
  715.83    29.5  731.95   27.42  760.41   15.95  786.18   27.06  852.86   29.78
  873.92   27.27 1220.93   24.94 1525.55   29.14 1679.23   39.59 1820.77   44.24
#Mann= 6 ,-1 , 0
-2476.07     .99       0  228.62     .01       0  674.73     .08       0
  731.95     .04       0  786.18     .08       0 1220.93     .99       0
#XS Ineff= 2 , 0
       0  715.83    29.5  852.86       0   29.78
Permanent Ineff=
       F       F
#Block Obstruct= 2 , 0
       0     675      27               0
Bank Sta=731.95,786.18
XS Rating Curve= 0 ,0
Exp/Cntr=0.5,0.3

Type RM Length L Ch R = 1 ,8193.117,366.4,367,368.73
BEGIN DESCRIPTION:
435s4u.  XS 3/4.  Combined structures 4, 5, and 6 into single structure.  Used lowest low chord and highest high chord.
Bank Station offset =      4356
 0.99 in LOB is area that is ineffective due to flow contracting for structure.
END DESCRIPTION:
XS GIS Cut Line= 6
     3258969.261    13867178.578     3258885.179    13867086.087
     3257754.397     13866470.48     3257279.265    13866165.004
     3257122.421    13866090.449     3256421.053    13865489.967
#Sta/Elev= 30
 -226.79   30.91  -30.47   28.86   69.35  31.223  182.66  27.255  626.72  27.033
  677.64  25.092  719.08  28.936  757.98  25.339  812.18  29.528  863.78  30.667
  1191.5  30.968 1523.35  31.909 1674.45  27.402 1760.02  26.953 1784.77  29.324
 1801.07   27.11 1810.91   22.72  1825.1   19.03 1827.69      16 1829.53   15.64
 1833.27   15.76 1835.63   18.72 1843.07   20.42  1855.3   26.75 2074.63   26.54
 2195.37   23.71 2494.78   28.99 2509.38    28.7 2690.03    39.7 2848.36   46.26
#Mann= 5 ,-1 , 0
 -226.79     .99       0  1191.5     .08       0 1801.07     .04       0
  1855.3     .08       0 2494.78     .99       0
#XS Ineff= 2 , 0
       0 1801.07      30  1855.3       0      30
Permanent Ineff=
       F       F
Bank Sta=1801.07,1855.3
XS Rating Curve= 0 ,0
Exp/Cntr=0.5,0.3