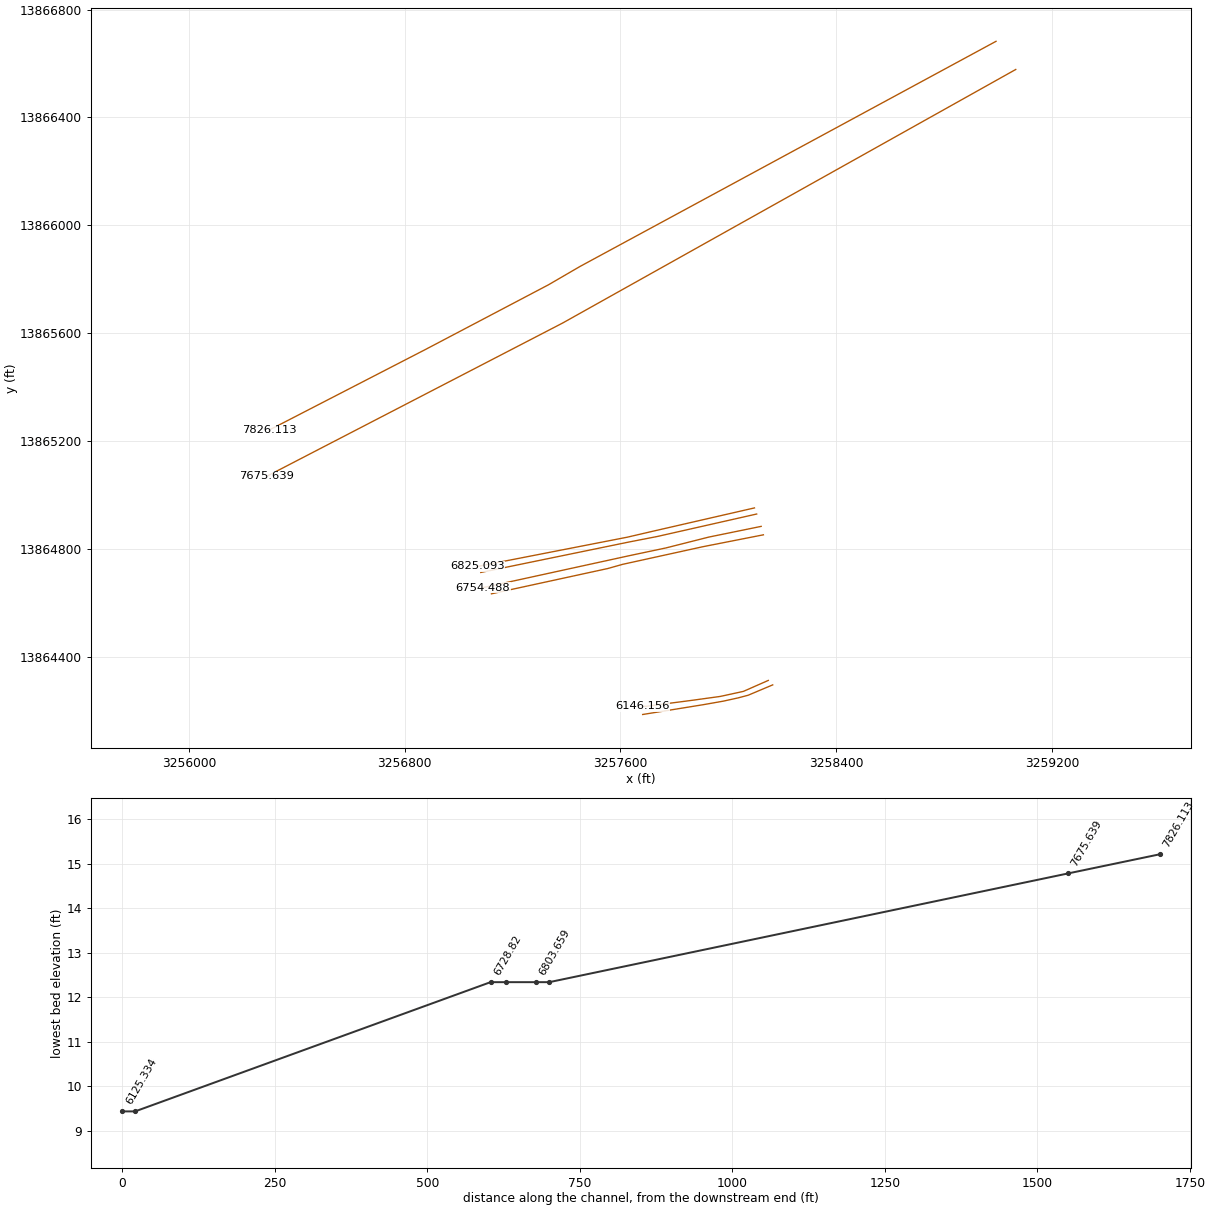
HEC-RAS study Q114-00-00.prj: Q114-00-00

--- Q114-00-00.g01 (geometry) --- (continued)

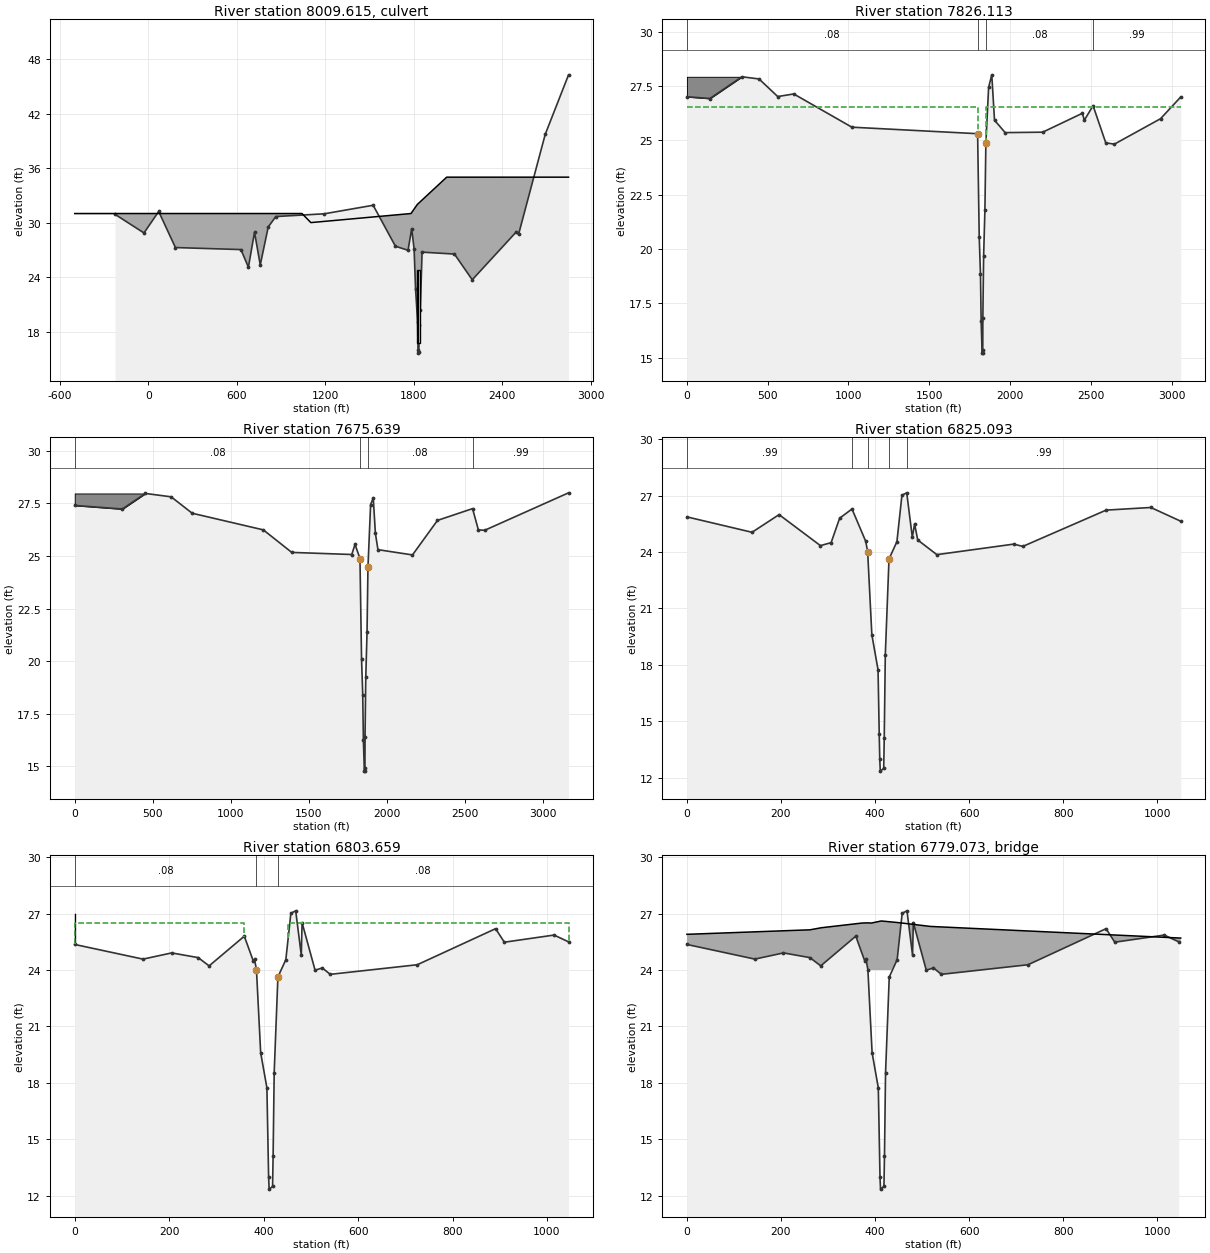
Type RM Length L Ch R = 2 ,8009.615,,,
BEGIN DESCRIPTION:
435s4,5,6- I-10 and Service Roads.
No data for DS Invert (used US data for the DS IN)
High chord set using LIDAR data because higher than surveyed top of road.  Elevation difference verified by survey digital photographs - at bridge, a continuous solid concrete wall extends ~ 2.5 ft above top of road.
High chord stopped at elevation 35 for plotting purposes.  Continues to near 50 for overpass.
u/s xsec stationing adjusted by 1186' to set enc stations at structure.
END DESCRIPTION:
Bridge Culvert--1,0,-1,-1, 0
Deck Dist Width WeirC Skew NumUp NumDn MinLoCord MaxHiCord MaxSubmerge Is_Ogee
54,260,2.6,0, 9, 7, , , 0.95, 0, 0,0,,
    -500       0     501    1041    1101    1780    1823    2022 2848.36
      31      31      31      31      30      31      32      35      35
                                                                        
       0    1040    1100    1779    1822    2021    3057
      31      31      30      31      32      35      35
                                                        
BR Coef=-1 , 0 , 0 ,, 0 ,,,0.8,0,,1,
WSPro=,,,, 1 ,,,, 0 ,,,, 0 ,,,,-1 ,-1 ,-1 , 0 , 0 , 0 , 0 , 0
Multiple Barrel Culv=2,8,10,270,0.013,0.5,1,10,1,16.74,16.99, 2,Culvert #1  , 0 ,48
 1824.32 1824.32 1835.44 1835.44
Culvert Bottom n=0.013
BC Design=,, 0 ,, 0 ,,,,,,
BC HTab HWMax=46.26
BC Use User HTab Curves=0
BC User HTab FreeFlow(D)= 0

Type RM Length L Ch R = 1 ,7826.113,151.72,150.48,150.28
BEGIN DESCRIPTION:
435s6d.  XS 2/4. Combined structures 4, 5, and 6 into single structure.  Used lowest low chord and highest high chord.
Bank Station offset =      3170
Manually extended ROB (2 points).
Block in LOB to close section
END DESCRIPTION:
XS GIS Cut Line= 6
     3258992.517    13866682.435     3257450.512    13865847.912
      3257406.08    13865822.089     3257332.861    13865779.534
     3256878.992    13865540.849 3256297.023067813865240.7729866
#Sta/Elev= 30
       0   27.01  142.46   26.93  340.62   27.93  446.57   27.83  562.25   27.02
   661.5   27.14 1021.09   25.61 1799.61   25.31 1809.65   20.55 1817.28   18.85
 1821.52   16.67  1827.6   15.22 1830.35   15.21 1831.51   15.37 1832.07   16.83
 1836.81   19.66 1844.87   21.82 1850.76   24.89 1867.75   27.44 1887.29   28.02
 1904.29   25.93 1970.14   25.36 2202.54   25.38 2448.12   26.25 2460.19   25.93
 2514.31    26.6 2592.94   24.89 2646.48   24.83    2932      26    3057      27
#Mann= 4 ,-1 , 0
       0     .08       0 1799.61     .04       0 1850.76     .08       0
 2514.31     .99       0
#XS Ineff= 2 , 0
       0 1799.61   26.56 1850.76       0   26.53
Permanent Ineff=
       F       F
#Block Obstruct= 2 , 0
       0  340.62   27.93               0
Bank Sta=1799.61,1850.76
XS Rating Curve= 0 ,0
Exp/Cntr=0.5,0.3

Type RM Length L Ch R = 1 ,7675.639,859.68,850.55,843.59
BEGIN DESCRIPTION:
Copy of 435s6d.  XS 1/4.  Adjusted elevations -0.43.
Combined structures 4, 5, and 6 into single structure.
Bank Station offset =      3143
Manually extended ROB (2 points).
0.99 in ROB is lateral channel.
END DESCRIPTION:
XS GIS Cut Line= 4
     3259065.632    13866577.985      3257385.51    13865637.805
     3256678.104    13865271.419 3256287.353464613865069.0380113
#Sta/Elev= 30
       0    27.4  305.07   27.23  452.59   27.97  617.35   27.81  752.27   27.03
 1207.59   26.24 1389.68   25.17  1773.8   25.07 1794.74   25.55 1826.43   24.88
 1836.47   20.12  1844.1   18.42 1848.34   16.24 1854.42   14.79 1857.17   14.78
 1858.33   14.94 1858.89    16.4 1863.63   19.23 1871.69   21.39 1877.58   24.46
 1894.57   27.44 1911.47   27.76 1925.29   26.07 1941.65    25.3 2162.74   25.05
 2322.66   26.69 2547.38   27.25 2584.57   26.24 2625.04   26.22    3162      28
#Mann= 4 ,-1 , 0
       0     .08       0 1826.43     .04       0 1877.58     .08       0
 2547.38     .99       0
#Block Obstruct= 2 , 0
       0  452.59   27.97               0
Bank Sta=1826.43,1877.58
XS Rating Curve= 0 ,0
Exp/Cntr=0.3,0.1

Type RM Length L Ch R = 1 ,6825.093,22.86,21.43,20.48
BEGIN DESCRIPTION:
435s7u.  XS 4/4.
Bank Station offset =      4589
Block on ROB to close section
END DESCRIPTION:
XS GIS Cut Line= 4
     3258096.793    13864952.239      3257721.48    13864866.084
     3257625.023    13864843.652      3257069.68    13864735.291
#Sta/Elev= 30
       0   25.87  138.46   25.05  195.99   25.99  283.92   24.34  306.63    24.5
  324.74    25.8  350.99   26.29  380.17   24.57  384.27   24.02   393.2    19.6
   406.4   17.73   408.9   14.31  410.03   12.98  411.16   12.34  418.39   12.48
  419.55   14.09  421.81   18.53  429.69   23.63  446.49   24.55  457.17   27.02
  467.36   27.15  479.24   24.79  484.11   25.49  490.77   24.64  531.44   23.86
  694.67   24.42  714.28    24.3   891.4   26.23  986.37   26.37 1049.92   25.64
#Mann= 5 ,-1 , 0
       0     .99       0  350.99     .08       0  384.27     .04       0
  429.69     .08       0  467.36     .99       0
#Block Obstruct= 2 , 0
       0                  981.03       0   26.38
Bank Sta=384.27,429.69
XS Rating Curve= 0 ,0
Exp/Cntr=0.5,0.3

Type RM Length L Ch R = 1 ,6803.659,48.88,49.17,49.78
BEGIN DESCRIPTION:
Copy of 435s7u.  XS 3/4.  Adjust elevations as needed.
Bank Station offset =      4588
Blocks added at LOB to contain flow -- ground does rise beyond cross section limits.  Ineffective elevations and stations are based on the location of high ground (XS 3/4 and u/s bridge section) and it is judged inappropriate to widen these stations.
IF WSEL>25, NOTE THAT ROAD DROPS TO 25' AT 100 YARDS FROM BRIDGE, BOTH SIDES.
END DESCRIPTION:
XS GIS Cut Line= 4
     3258104.935    13864929.589     3257735.808    13864846.158
      3257630.75    13864825.644     3257081.971    13864712.912
#Sta/Elev= 30
       0   25.36  144.51   24.58  205.28   24.91  261.44   24.66  284.58   24.22
  359.07    25.8  378.44   24.46  380.72   24.57  384.82   24.02  393.75    19.6
  406.95   17.73  410.58   12.98  411.71   12.34  418.94   12.48   420.1   14.09
  422.36   18.53  430.24   23.63  447.04   24.55  457.72   27.02  467.91   27.15
  479.79   24.79  481.45   26.52  508.96   23.99  524.31   24.11  541.04   23.77
  725.31   24.28  891.22    26.2  909.75   25.48 1014.98   25.86 1045.72    25.5
#Mann= 3 , 0 , 0
       0     .08       0  384.82     .04       0  430.24     .08       0
#XS Ineff= 2 , 0
       0     358    26.5     452       0   26.51
Permanent Ineff=
       F       F
#Block Obstruct= 2 , 0
       0       1      27    1045       0      27
Bank Sta=384.82,430.24
XS Rating Curve= 0 ,0
Exp/Cntr=0.5,0.3

Type RM Length L Ch R = 3 ,6779.073,,,
BEGIN DESCRIPTION:
435s7-Needle Point Rd.  Ineffective elevations and stations are based on the location of high ground (XS 3/4 and u/s bridge section) and it is judged inappropriate to widen these stations.
END DESCRIPTION:
Bridge Culvert--1,0,-1,-1, 0
Deck Dist Width WeirC Skew NumUp NumDn MinLoCord MaxHiCord MaxSubmerge Is_Ogee
7.585,34,2.6,0, 12, 12, , , 0.95, 0, 0,0,,
       0  261.76  285.77  372.29  384.11   392.2  413.37  434.25   442.6  454.12
  517.77    1050
    25.9   26.14   26.25    26.5   26.51    26.5   26.61   26.56   26.54   26.51
   26.32    25.7
                                      24      24      24      24      24
                
       0  258.76  282.77  369.29  381.11   389.2  410.37  431.25   439.6  451.12
  514.77    1050
    25.9   26.14   26.25    26.5   26.51    26.5   26.61   26.56   26.54   26.51
   26.32    25.7
                                      24      24      24      24      24
                
BR Coef=-1 , 0 , 0 ,, 0 ,,,0.8,0,,1,
WSPro=,,,, 1 ,,,, 0 ,,,, 0 ,,,,-1 ,-1 ,-1 , 0 , 0 , 0 , 0 , 0
BC Design=,, 0 ,, 0 ,,,,,,
BC HTab HWMax=27.15
BC Use User HTab Curves=0
BC User HTab FreeFlow(D)= 0

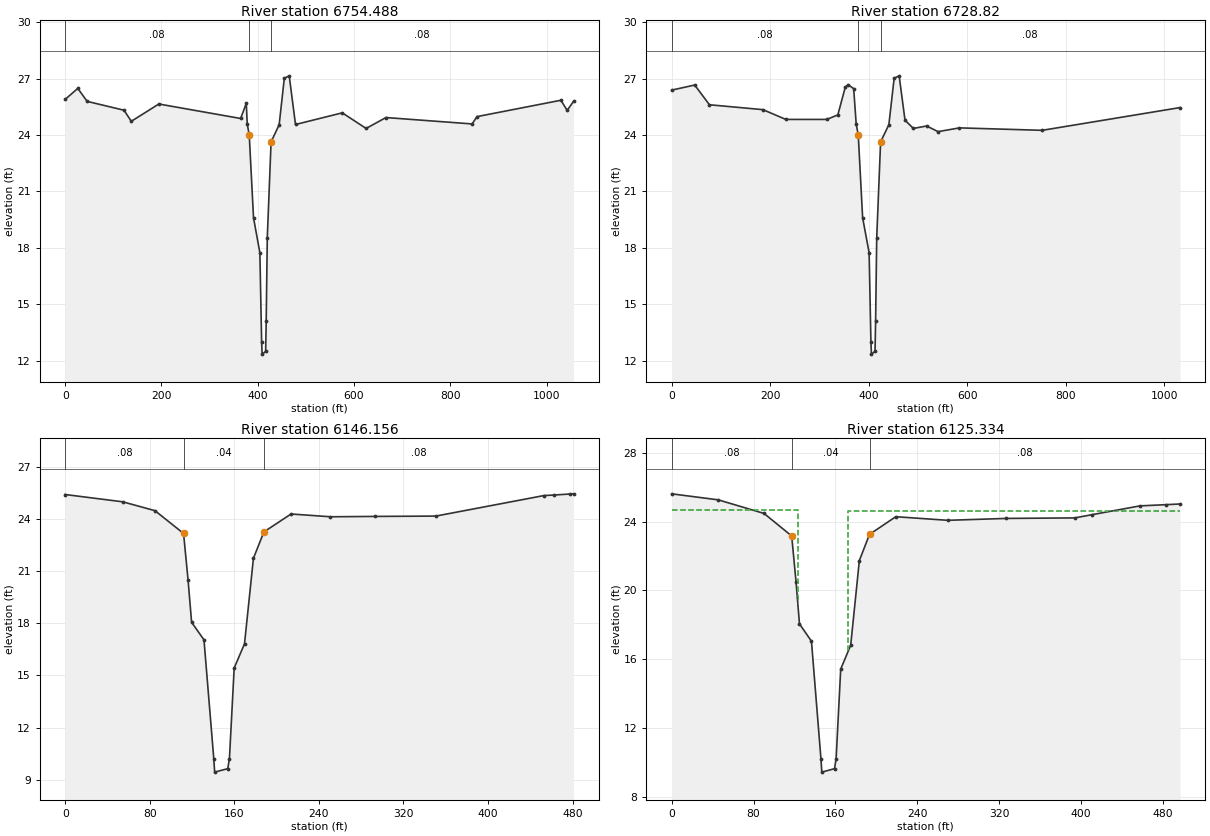
Type RM Length L Ch R = 1 ,6754.488,25.42,25.67,26.08
BEGIN DESCRIPTION:
Copy of 435s7u.  XS 2/4.  Adjust elevations as needed.
Bank Station offset =      4591
END DESCRIPTION:
XS GIS Cut Line= 5
     3258121.602    13864883.753     3257927.843    13864844.168
     3257768.755    13864803.886      3257634.08    13864775.415
     3257090.305     13864656.66
#Sta/Elev= 30
       0    25.9    26.2   26.48   45.61   25.79  122.12   25.32  137.31   24.73
  194.53   25.65   364.5   24.88  376.23   25.69  378.21   24.57  382.31   24.02
  391.24    19.6  404.44   17.73  408.07   12.98   409.2   12.34  416.43   12.48
  417.59   14.09  419.85   18.53  427.73   23.63  444.53   24.55  455.21   27.02
   465.4   27.15  478.47   24.56  575.65   25.18  625.16   24.35  666.38   24.93
  845.37   24.59   855.6   24.98 1029.89   25.85 1042.86   25.31 1056.11   25.79
#Mann= 3 , 0 , 0
       0     .08       0  382.31     .04       0  427.73     .08       0
#XS Ineff= 2 , 0
       0     370      25  446.75       0      25
Permanent Ineff=
       F       F
Bank Sta=382.31,427.73
XS Rating Curve= 0 ,0
Exp/Cntr=0.5,0.3

Type RM Length L Ch R = 1 ,6728.82 ,577.87,582.66,584.91
BEGIN DESCRIPTION:
Copy of 435s7u.  XS 1/4.  Adjust elevations as needed.
Bank Station offset =      4594
END DESCRIPTION:
XS GIS Cut Line= 5
     3258129.936    13864852.502     3257904.895    13864808.237
     3257607.749    13864742.965     3257552.826    13864727.496
     3257121.557    13864633.742
#Sta/Elev= 30
       0   26.39   46.78   26.66   76.67   25.61   185.2   25.35  231.81   24.83
  314.84   24.83  337.32   25.07  352.41   26.54  357.96   26.68  369.51   26.47
  374.64   24.57  378.74   24.02  387.67    19.6  400.87   17.73   404.5   12.98
  405.63   12.34  412.86   12.48  414.02   14.09  416.28   18.53  424.16   23.63
  440.96   24.55  451.64   27.02  461.83   27.15  473.71   24.79  490.63   24.35
  517.59   24.48  540.85   24.18  584.29   24.38   752.2   24.25 1031.99   25.46
#Mann= 3 , 0 , 0
       0     .08       0  378.74     .04       0  424.16     .08       0
Bank Sta=378.74,424.16
XS Rating Curve= 0 ,0
Exp/Cntr=0.3,0.1

Type RM Length L Ch R = 1 ,6146.156,20.25,20.82,20.18
BEGIN DESCRIPTION:
Copy of 435s8d.  XS 4/4.  Adjust elevations as needed.
Bank Station offset =      4859
END DESCRIPTION:
XS GIS Cut Line= 6
     3258148.007    13864312.547     3258055.744    13864271.907
     3257970.071    13864253.234     3257866.824    13864238.956
     3257698.773    13864216.988     3257680.101     13864215.89
#Sta/Elev= 23
       0   25.41   54.47   24.99   84.95   24.48  111.97   23.17   116.2   20.52
  119.58   18.06  131.29   17.05  140.59   10.19  141.39    9.44  153.81    9.64
  155.38   10.22  159.87   15.43  169.63   16.82  178.07   21.74     188   23.26
  213.67   24.29  250.97   24.13  292.73   24.15  350.68   24.17  452.89   25.35
  462.21   25.38  477.81   25.44  480.92   25.45
#Mann= 3 , 0 , 0
       0     .08       0  111.97     .04       0     188     .08       0
Bank Sta=111.97,188
XS Rating Curve= 0 ,0
Exp/Cntr=0.5,0.3

Type RM Length L Ch R = 1 ,6125.334,29.02,28.45,27.48
BEGIN DESCRIPTION:
Copy of 435s8d.  XS 3/4.  Adjust elevations as needed.
Bank Station offset =      4853
END DESCRIPTION:
XS GIS Cut Line= 6
     3258164.483    13864296.071     3258073.318    13864257.628
     3258035.973    13864247.743     3257981.055     13864235.66
     3257906.366     13864222.48     3257682.297    13864186.234
#Sta/Elev= 23
       0   25.62   45.51   25.27   90.23   24.48  117.25   23.17  121.48   20.52
  124.86   18.06  136.57   17.05  145.87   10.19  146.67    9.44  159.09    9.64
  160.66   10.22  165.15   15.43  174.91   16.82  183.35   21.74  193.28   23.26
  218.95   24.29  269.64   24.08   326.8   24.19  393.88   24.22  410.86   24.41
  457.63   24.92  483.27   24.99  496.63   25.03
#Mann= 3 , 0 , 0
       0     .08       0  117.25     .04       0  193.28     .08       0
#XS Ineff= 2 , 0
       0  123.28   24.69  172.37       0   24.65
Permanent Ineff=
       F       F
Bank Sta=117.25,193.28
XS Rating Curve= 0 ,0
Exp/Cntr=0.5,0.3