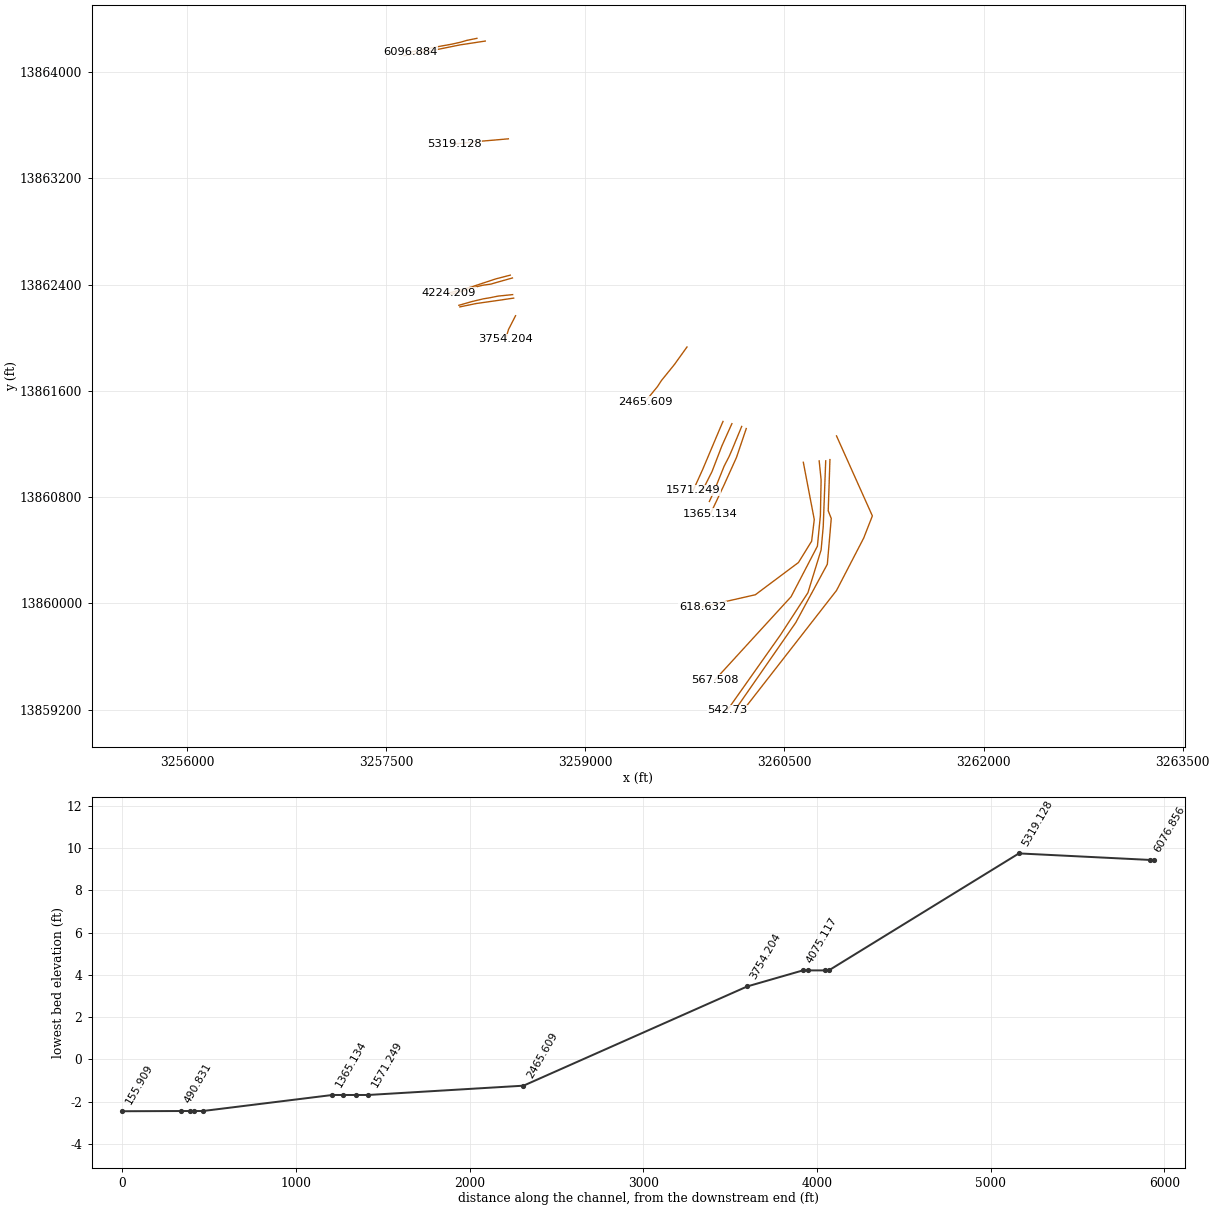
HEC-RAS study Q114-00-00.prj: Q114-00-00

--- Q114-00-00.g01 (geometry) --- (continued)

Type RM Length L Ch R = 3 ,6111.109,,,
BEGIN DESCRIPTION:
435s8 - Pecan Forest
Shift the centerline: -7ft
END DESCRIPTION:
Bridge Culvert--1,0,-1,-1, 0
Deck Dist Width WeirC Skew NumUp NumDn MinLoCord MaxHiCord MaxSubmerge Is_Ogee
7.25,14,2.6,0, 9, 9, , , 0.95, 0, 0,0,,
   45.51   90.23   95.15   108.5  126.57  168.57  181.27  196.84  218.95
   25.27   24.48   24.72   24.67   24.69   24.65    24.8   24.85   24.29
                                   23.48   23.48
   77.33   89.98   94.15   107.5  125.57  167.57  180.27  195.84   218.7
   24.85   24.48   24.72   24.67   24.69   24.65    24.8   24.85   24.29
                                   23.48   23.48
Pier Skew, UpSta & Num, DnSta & Num=  ,140, 4 ,139, 4 , 3 , 3 , 0 ,0,
       1       1     1.4     1.4
      -5   22.08   22.08   23.48
       1       1     1.4     1.4
      -5   22.08   22.08   23.48
Pier Skew, UpSta & Num, DnSta & Num=  ,154.32, 4 ,153.32, 4 , 3 , 3 , 0 ,0,
       1       1     1.4     1.4
      -5   22.08   22.08   23.48
       1       1     1.4     1.4
      -5   22.08   22.08   23.48
BR Coef=-1 , 0 , 0 ,, 0 ,,,0.8,-1,,1,
WSPro=,,,, 1 ,,,, 0 ,,,, 0 ,,,,-1 ,-1 ,-1 , 0 , 0 , 0 , 0 , 0
BC Design=,, 0 ,, 0 ,,,,,,
BC HTab HWMax=25.62
BC Use User HTab Curves=0
BC User HTab FreeFlow(D)= 0

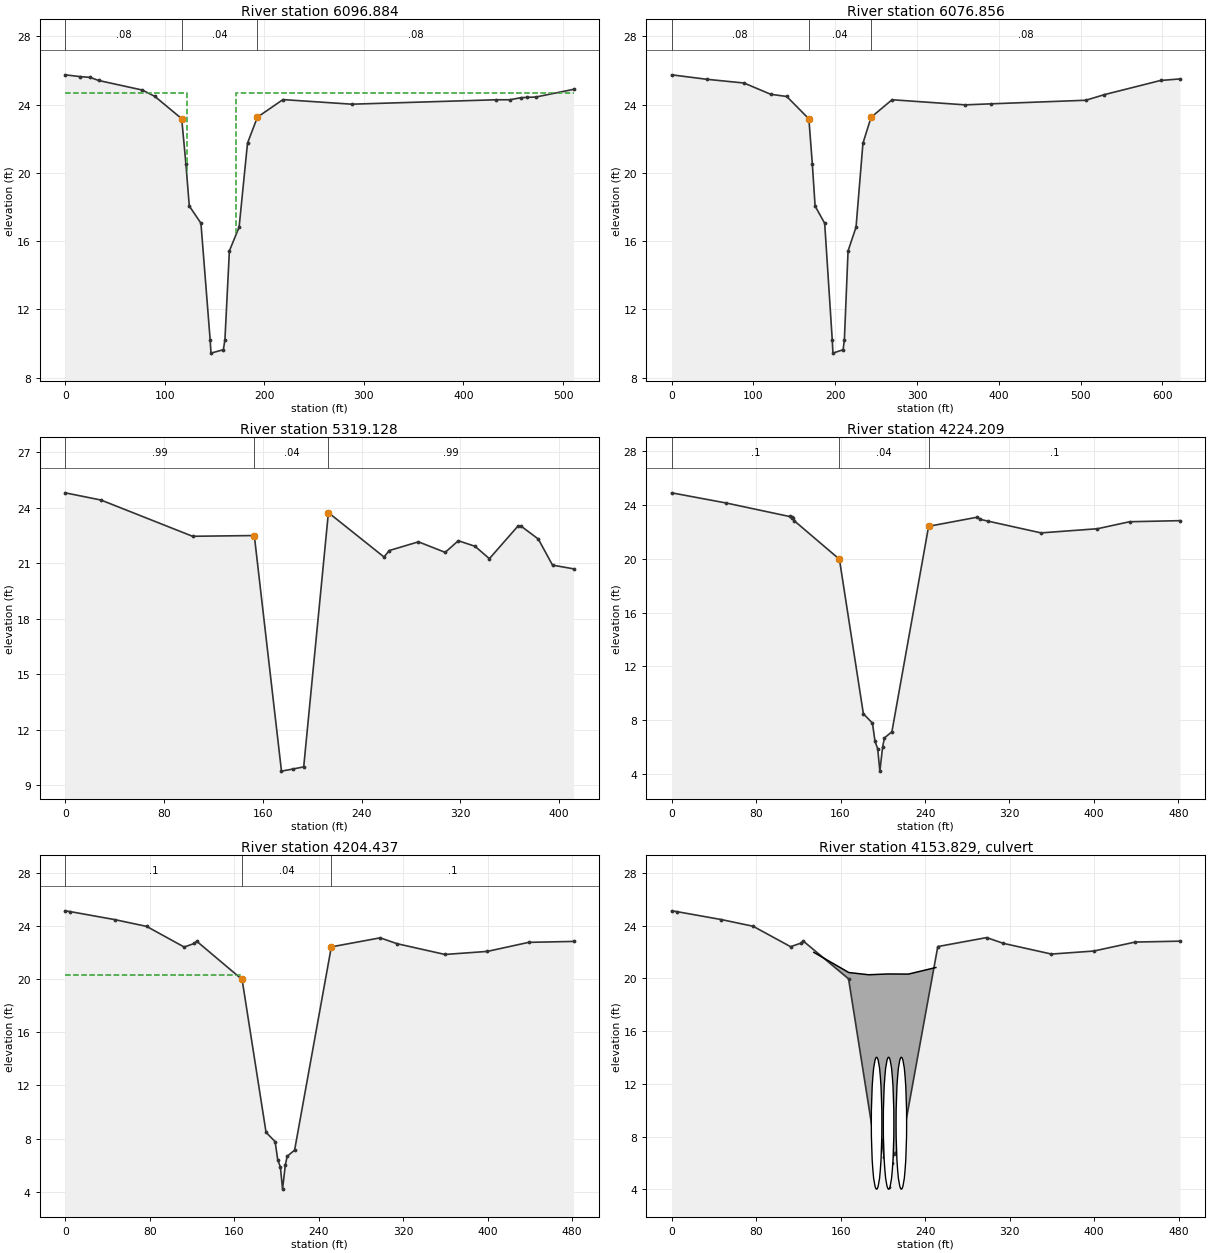
Type RM Length L Ch R = 1 ,6096.884,21.78,20.03,18.56
BEGIN DESCRIPTION:
Copy of 435s8d.  XS 2/4.  Adjust elevations as needed.
Bank Station offset =      4854
END DESCRIPTION:
XS GIS Cut Line= 6
     3258184.254    13864255.431     3258108.466    13864240.054
     3258059.039    13864225.775     3257995.334    13864211.496
      3257903.07    13864195.021     3257684.494    13864152.184
#Sta/Elev= 26
       0   25.74   14.38   25.64   25.05   25.59   33.51   25.41   77.33   24.85
   89.98   24.48     117   23.17  121.23   20.52  124.61   18.06  136.32   17.05
  145.62   10.19  146.42    9.44  158.84    9.64  160.41   10.22   164.9   15.43
  174.66   16.82   183.1   21.74  193.03   23.26   218.7   24.29  287.79   24.02
  433.12   24.28  446.65   24.28  457.71    24.4  463.78   24.42  472.74   24.44
  510.55   24.89
#Mann= 3 , 0 , 0
       0     .08       0     117     .04       0  193.03     .08       0
#XS Ineff= 2 , 0
       0     122   24.65     172       0   24.65
Permanent Ineff=
       F       F
Bank Sta=117,193.03
XS Rating Curve= 0 ,0
Exp/Cntr=0.5,0.3

Type RM Length L Ch R = 1 ,6076.856,763.58,757.73,751.99
BEGIN DESCRIPTION:
435s8d.  XS 1/4.
Bank Station offset =      4803
END DESCRIPTION:
XS GIS Cut Line= 4
     3258247.107     13864234.91     3258058.028    13864206.189
     3257862.966    13864166.698     3257635.593    13864124.814
#Sta/Elev= 24
       0   25.75   42.66   25.49   88.41   25.27   121.1   24.61  140.72   24.48
  167.74   23.17  171.97   20.52  175.35   18.06  187.06   17.05  196.36   10.19
  197.16    9.44  209.58    9.64  211.15   10.22  215.64   15.43   225.4   16.82
  233.84   21.74  243.77   23.26  269.44   24.29  358.77   23.99  390.27   24.05
  506.31   24.26  529.09   24.59  597.78   25.42  621.47   25.51
#Mann= 3 , 0 , 0
       0     .08       0  167.74     .04       0  243.77     .08       0
Bank Sta=167.74,243.77
XS Rating Curve= 0 ,0
Exp/Cntr=0.3,0.1

Type RM Length L Ch R = 1 ,5319.128,1082.36,1094.92,1100.54
BEGIN DESCRIPTION:
435v8
Bank Station offset =      4825
Block added in ROB to close cross section
Per field survey data, LIDAR points were removed between 213.11 and 258.14.
END DESCRIPTION:
XS GIS Cut Line= 4
      3258421.06    13863498.625     3258316.515    13863489.367
     3258204.025    13863479.793     3258011.357    13863459.449
#Sta/Elev= 20
       0    24.8   28.97   24.41  103.11   22.45  153.11   22.49  175.11    9.75
  184.11    9.86  193.11    9.98  213.11   23.73  258.14   21.33  262.42   21.68
  286.01   22.15  307.67   21.58   318.3   22.21   331.8   21.91  343.46   21.24
  366.69   23.01  368.89   23.01  383.09    22.3  394.57   20.89  411.59   20.69
#Mann= 3 , 0 , 0
       0     .99       0  153.11     .04       0  213.11     .99       0
#Block Obstruct= 2 , 0
       0                  368.89       0   23.01
Bank Sta=153.11,213.11
XS Rating Curve= 0 ,0
Exp/Cntr=0.3,0.1

Type RM Length L Ch R = 1 ,4224.209,26.35,19.77,12.23
BEGIN DESCRIPTION:
435s9u.  XS 4/4.
Bank Station offset =      4803
END DESCRIPTION:
XS GIS Cut Line= 5
     3258435.684    13862472.025     3258324.225     13862443.11
     3258159.937    13862388.705     3258149.055    13862384.282
     3257973.568    13862337.485
#Sta/Elev= 24
       0   24.91   51.84   24.15  111.66   23.15  113.63   23.07  114.15   23.08
  115.15   23.03     116   22.84  158.92   19.97   181.6    8.48  190.21    7.78
  192.65    6.42  195.16    5.88  197.24    4.21  199.85    6.02  201.59    6.68
  208.64    7.14  243.43   22.42  289.67    23.1  292.12   22.94  299.96    22.8
  349.97   21.93  403.42   22.24  433.81   22.76  481.58   22.84
#Mann= 3 , 0 , 0
       0      .1       0  158.92     .04       0  243.43      .1       0
Bank Sta=158.92,243.43
XS Rating Curve= 0 ,0
Exp/Cntr=0.5,0.3

Type RM Length L Ch R = 1 ,4204.437,99.69,101.22,100.4
BEGIN DESCRIPTION:
Copy of 435s9u.  XS 3/4.  Adjust elevations as needed.
Bank Station offset =      4794
END DESCRIPTION:
XS GIS Cut Line= 6
     3258451.654     13862450.69     3258313.513    13862411.705
     3258291.479    13862404.925      3258227.07    13862395.603
     3258188.933     13862386.28      3257987.23    13862326.109
#Sta/Elev= 23
       0   25.13    4.86   25.07   46.86   24.47   77.11   23.96  112.65   22.41
  122.43   22.68  124.61   22.84  167.53   19.97  190.21    8.48  198.82    7.78
  201.26    6.42  203.77    5.88  205.85    4.21  208.46    6.02   210.2    6.68
  217.25    7.14  252.04   22.42  298.28    23.1  314.25   22.66  359.69   21.85
  399.79   22.08  438.92   22.76  481.42   22.83
#Mann= 3 , 0 , 0
       0      .1       0  167.53     .04       0  252.04      .1       0
#XS Ineff= 2 , 0
       0  167.53   20.28  252.04       0   20.33
Permanent Ineff=
       F       F
Bank Sta=167.53,252.04
XS Rating Curve= 0 ,0
Exp/Cntr=0.5,0.3

Type RM Length L Ch R = 2 ,4153.829,,,
BEGIN DESCRIPTION:
435s9- Sarah Lane (3 Cylinder Culverts)
END DESCRIPTION:
Bridge Culvert--1,0,-1,-1, 0
Deck Dist Width WeirC Skew NumUp NumDn MinLoCord MaxHiCord MaxSubmerge Is_Ogee
40,20.8,2.6,0, 6, 6, , , 0.95, 0, 0,0,,
  134.64  167.76   186.6   204.7  224.22  250.19
   21.98   20.45   20.28   20.34   20.33   20.83
       0       0       0       0       0       0
  117.64  150.76   169.6   187.7  207.22  233.19
   21.98   20.45   20.28   20.34   20.33   20.83
       0       0       0       0       0       0
BR Coef=-1 , 0 , 0 ,, 0 ,,,0.8,0,,1,
WSPro=,,,, 1 ,,,, 0 ,,,, 0 ,,,,-1 ,-1 ,-1 , 0 , 0 , 0 , 0 , 0
Multiple Barrel Culv=1,10,,36.8,0.015,0.5,1,1,1,4.02,4.26, 3,Culvert #1  , 0 ,32.21
  194.08   178.2  205.44  189.92  217.52  201.46
Culvert Bottom n=0.015
BC Design=,, 0 ,, 0 ,,,,,,
BC HTab HWMax=25.13
BC Use User HTab Curves=0
BC User HTab FreeFlow(D)= 0

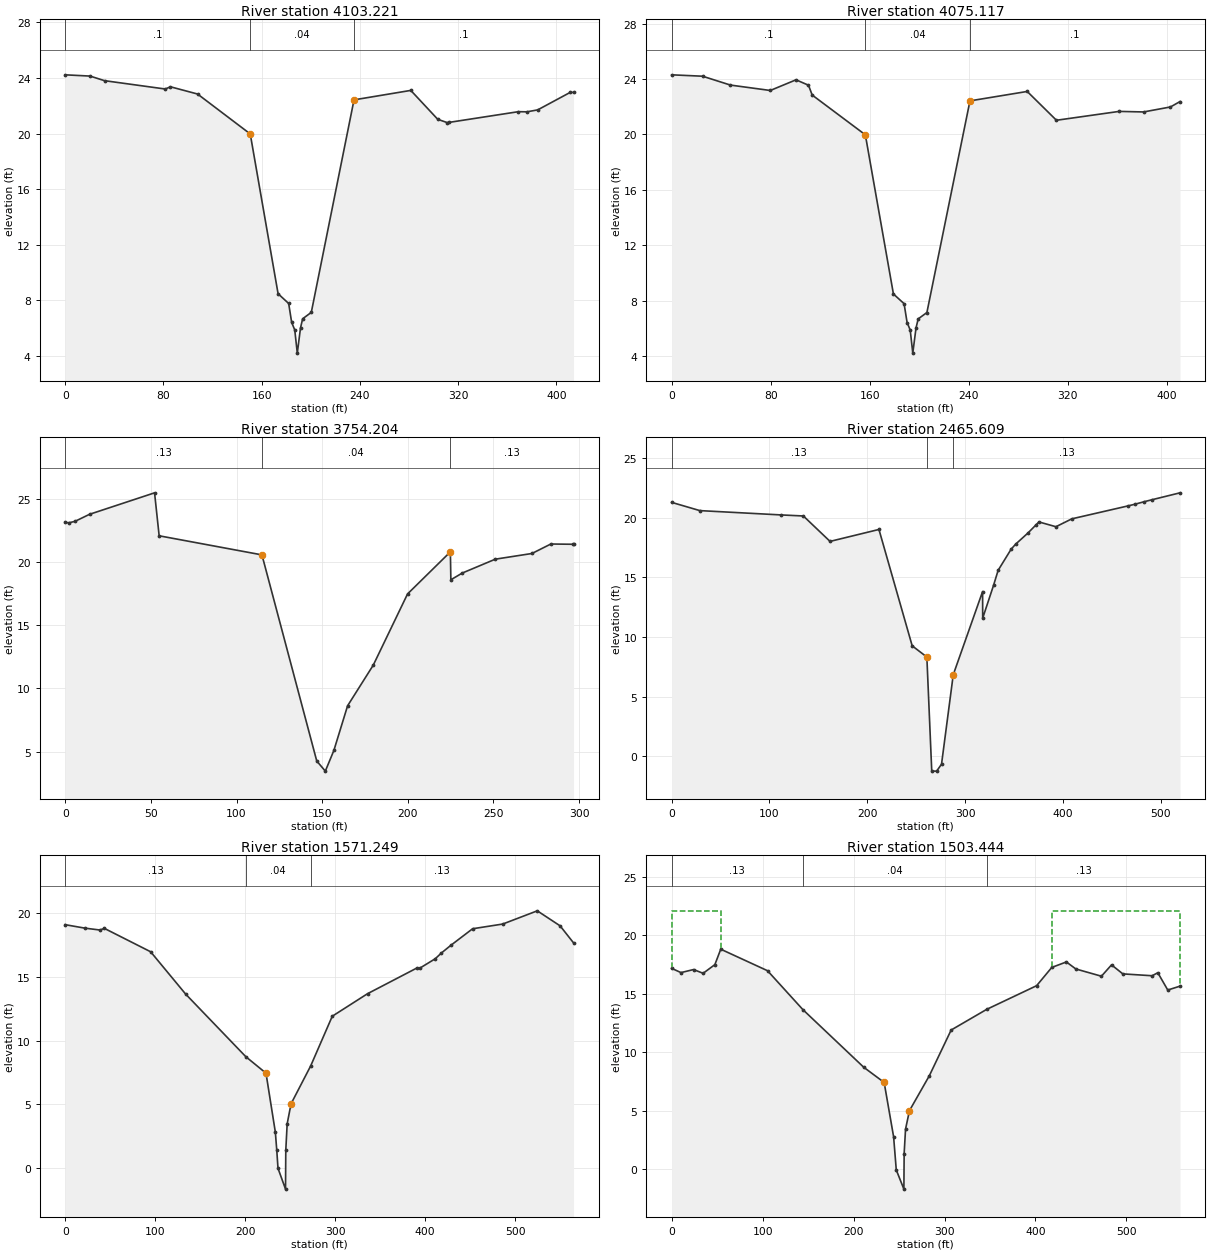
Type RM Length L Ch R = 1 ,4103.221,29.97,28.1,26.39
BEGIN DESCRIPTION:
Copy of 435s9u.  XS 2/4.  Adjust elevations as needed.
Bank Station offset =      4811
END DESCRIPTION:
XS GIS Cut Line= 6
     3258453.349    13862325.261     3258344.023    13862314.244
     3258281.309    13862301.532     3258230.459    13862293.057
     3258145.711    13862272.717     3258048.249     13862244.75
#Sta/Elev= 25
       0   24.22   20.24   24.13      32    23.8   81.48    23.2   85.71   23.36
  107.77   22.84  150.69   19.97  173.37    8.48  181.98    7.78  184.42    6.42
  186.93    5.88  189.01    4.21  191.62    6.02  193.36    6.68  200.41    7.14
   235.2   22.42  281.44    23.1  303.41   21.02  311.28   20.78  312.58    20.8
  369.06   21.57  376.05   21.56   384.8    21.7   411.1   22.95  413.97   22.96
#Mann= 3 , 0 , 0
       0      .1       0  150.69     .04       0   235.2      .1       0
#XS Ineff= 2 , 0
       0  150.69   17.27   235.2       0    17.3
Permanent Ineff=
       F       F
Bank Sta=150.69,235.2
XS Rating Curve= 0 ,0
Exp/Cntr=0.5,0.3

Type RM Length L Ch R = 1 ,4075.117,298.07,320.91,323.83
BEGIN DESCRIPTION:
Copy of 435s9u.  XS 1/4.  Adjust elevations as needed.
Bank Station offset =      4805
END DESCRIPTION:
XS GIS Cut Line= 5
     3258460.977    13862298.989      3258351.65    13862282.887
     3258274.529    13862271.869      3258179.61     13862258.31
     3258055.877    13862232.885
#Sta/Elev= 23
       0    24.3   24.93    24.2   47.47   23.56   79.65   23.17  100.44   23.94
  110.51   23.55  113.52   22.84  156.44   19.97  179.12    8.48  187.73    7.78
  190.17    6.42  192.68    5.88  194.76    4.21  197.37    6.02  199.11    6.68
  206.16    7.14  240.95   22.42  287.19    23.1   310.8   21.02  361.49   21.66
  381.18   21.62  402.89   21.98  410.61   22.37
#Mann= 3 , 0 , 0
       0      .1       0  156.44     .04       0  240.95      .1       0
Bank Sta=156.44,240.95
XS Rating Curve= 0 ,0
Exp/Cntr=0.3,0.1

Type RM Length L Ch R = 1 ,3754.204,1256.93,1288.59,1308.59
BEGIN DESCRIPTION:
435v9
Bank Station offset =      4848
END DESCRIPTION:
XS GIS Cut Line= 4
 3258475.275615313862166.4324443 3258429.248520613862076.4391696
  3258422.378805  13862063.38671 3258399.708743513861987.8198381
#Sta/Elev= 21
       0   23.13    2.11    23.1    5.68   23.21   14.19   23.77   52.16   25.47
   54.84   22.07  114.84   20.56  146.84    4.25  151.84    3.45  156.84    5.09
  164.84    8.62  179.84   11.84  199.84   17.47  224.84    20.8  225.12   18.59
  231.74   19.12  251.07   20.22  272.45   20.67  283.48   21.42   296.2    21.4
  296.73   21.39
#Mann= 3 , 0 , 0
       0     .13       0  114.84     .04       0  224.84     .13       0
Bank Sta=114.84,224.84
XS Rating Curve= 0 ,0
Exp/Cntr=0.3,0.1

Type RM Length L Ch R = 1 ,2465.609,865.7,894.36,876.28
BEGIN DESCRIPTION:
435v10
Bank Station offset =      4729
END DESCRIPTION:
XS GIS Cut Line= 5
     3259766.461     13861930.94     3259671.485    13861798.543
     3259573.745    13861678.061     3259544.177    13861632.612
     3259450.584    13861518.545
#Sta/Elev= 28
       0   21.27   28.78   20.58  111.44   20.22  134.67   20.13  161.97      18
  211.97      19  245.97    9.25  260.97    8.31  265.97   -1.25  270.97   -1.25
  275.97    -.67  287.97    6.83  317.97    13.8  318.08   11.57  329.14   14.31
  333.88   15.58   347.1   17.34  351.78   17.77  364.45   18.71   372.3   19.36
  375.61   19.63  392.97   19.23   409.2   19.89  466.47   20.97  473.95   21.12
  483.46   21.33  491.16   21.49  519.85   22.07
#Mann= 3 , 0 , 0
       0     .13       0  260.97     .04       0  287.97     .13       0
Bank Sta=260.97,287.97
XS Rating Curve= 0 ,0
Exp/Cntr=0.3,0.1

Type RM Length L Ch R = 1 ,1571.249,66.61,67.81,68.93
BEGIN DESCRIPTION:
435s10u.  XS 4/4.
Bank Station offset =      4755
END DESCRIPTION:
XS GIS Cut Line= 4
     3260037.642    13861370.235     3260018.815    13861326.941
     3259884.113    13861007.456     3259813.257    13860851.695
#Sta/Elev= 28
       0   19.11   21.71   18.84   38.62   18.69   43.52   18.82   94.96   16.98
  133.89   13.65  200.72    8.73   223.2    7.43  233.59    2.79  235.18    1.36
  236.53    -.05   244.9   -1.69  245.19    1.35  246.72    3.44  251.04    5.02
  272.86       8  296.87   11.91  336.03   13.68  390.85    15.7  393.93   15.68
  411.33   16.43  418.13   16.88  428.73   17.49  452.85   18.79  486.34   19.16
  524.75    20.2  550.09   19.02  565.05   17.68
#Mann= 3 ,-1 , 0
       0     .13       0  200.72     .04       0  272.86     .13       0
Bank Sta=223.2,251.04
XS Rating Curve= 0 ,0
Exp/Cntr=0.5,0.3

Type RM Length L Ch R = 1 ,1503.444,80.76,76.38,76.1
BEGIN DESCRIPTION:
Copy of 435s10u.  XS 3/4.  Adjust elevations as needed.
Bank Station offset =      4745
END DESCRIPTION:
XS GIS Cut Line= 4
     3260104.583      13861353.5     3260028.716    13861185.031
     3259955.081    13860993.134     3259879.215    13860842.516
#Sta/Elev= 30
       0   17.18   10.26   16.82   24.06   17.08   34.58   16.76    47.5    17.5
   53.96   18.82   105.4   16.98  144.33   13.65  211.16    8.73  233.64    7.43
  244.03    2.79  246.97    -.05  255.34   -1.69  255.63    1.35  257.16    3.44
  261.48    5.02   283.3       8  307.31   11.91  346.47   13.68  401.29    15.7
  417.95   17.26  434.01   17.73  444.41   17.13  472.55   16.51  483.67   17.48
  496.09   16.71  528.38   16.55  534.54   16.81  545.49   15.33  558.95   15.66
#Mann= 3 ,-1 , 0
       0     .13       0  144.33     .04       0  346.47     .13       0
#XS Ineff= 2 , 0
       0   53.96   22.05  417.95       0    22.1
Permanent Ineff=
       F       F
Bank Sta=233.64,261.48
XS Rating Curve= 0 ,0
Exp/Cntr=0.5,0.3

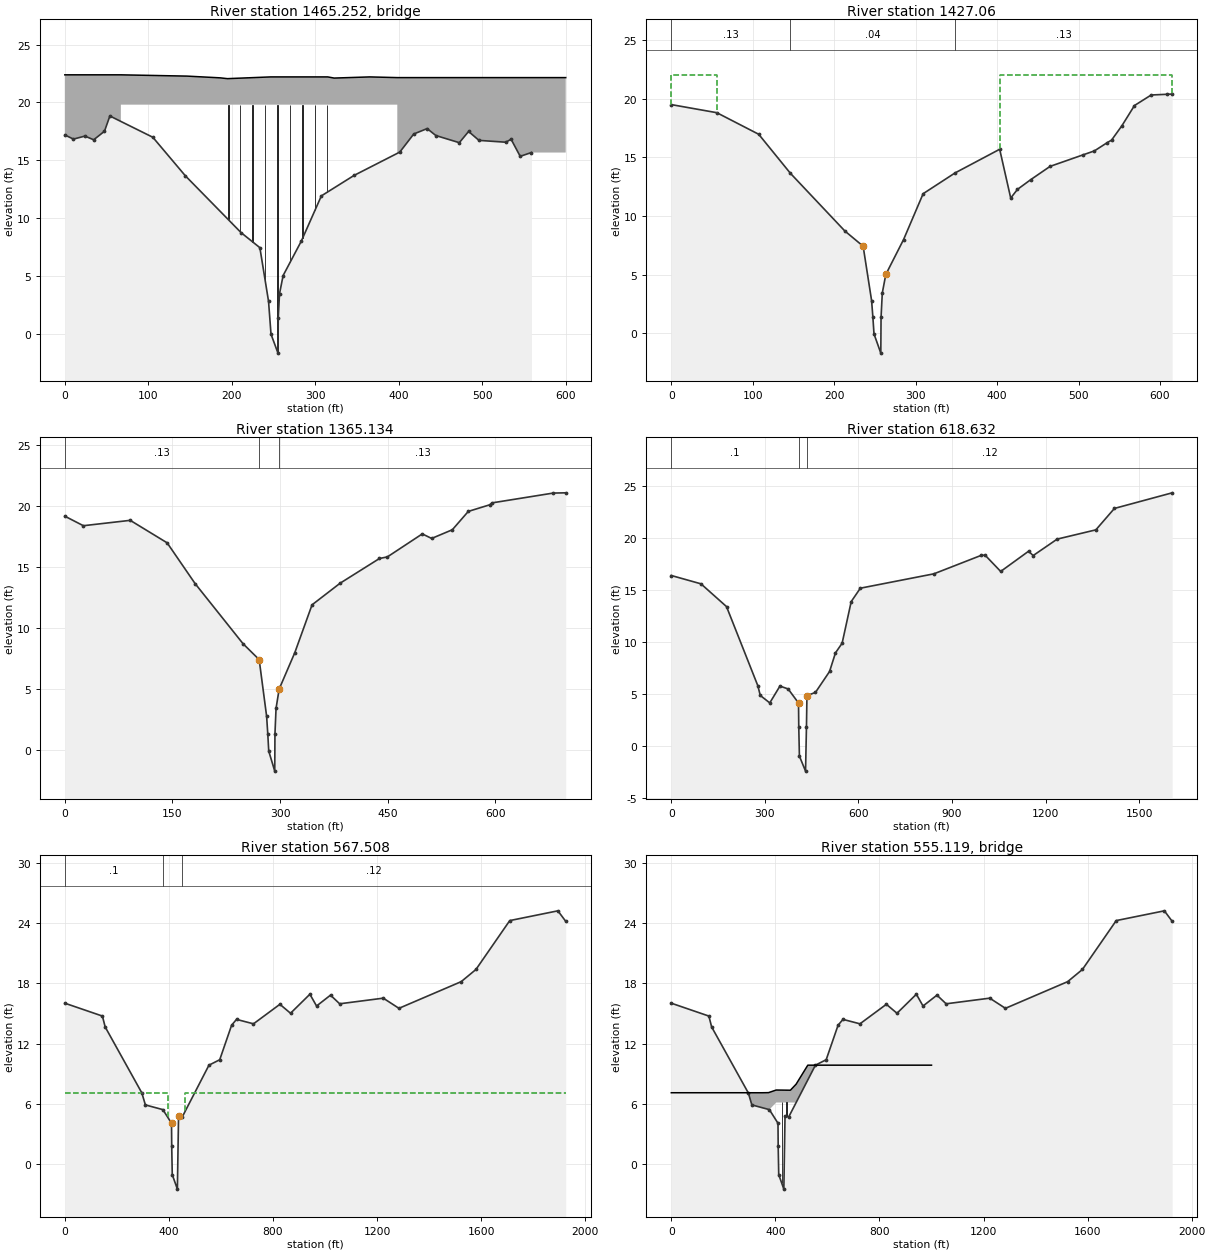
Type RM Length L Ch R = 3 ,1465.252,,,
BEGIN DESCRIPTION:
435s10- Dayton-Goose Creek RR
No survey note.
Shift the centerline: -5ft
Ineffective flow on ROB stationed based on high ground in XS 2/4.
END DESCRIPTION:
Bridge Culvert--1,0,-1,-1, 0
Deck Dist Width WeirC Skew NumUp NumDn MinLoCord MaxHiCord MaxSubmerge Is_Ogee
30.2,16,2.6,0, 11, 11, , , 0.95, 0, 0,0,,
       0    67.1  146.07  185.97  194.78  246.54  314.97  322.58  365.24  398.27
     600
   22.38   22.38   22.27   22.12   22.05    22.2    22.2    22.1    22.2   22.14
   22.14
            19.8    19.8    19.8    19.8    19.8    19.8    19.8    19.8    19.8
        
       0    69.1  148.07  187.97  196.78  248.54  316.97  324.58  367.24  400.27
     650
   22.38   22.38   22.27   22.12   22.05    22.2    22.2    22.1    22.2   22.14
   22.14
            19.8    19.8    19.8    19.8    19.8    19.8    19.8    19.8    19.8
        
Pier Skew, UpSta & Num, DnSta & Num=  ,195.7, 2 ,197.7, 2 , 0 , 0 , 0 ,0,
       1       1
      -3   19.81
       1       1
      -3   19.81
Pier Skew, UpSta & Num, DnSta & Num=  ,209.85, 2 ,211.85, 2 , 0 , 0 , 0 ,0,
       1       1
      -3   19.81
       1       1
      -3   19.81
Pier Skew, UpSta & Num, DnSta & Num=  ,224.86, 2 ,226.86, 2 , 0 , 0 , 0 ,0,
       1       1
      -3   19.81
       1       1
      -3   19.81
Pier Skew, UpSta & Num, DnSta & Num=  ,239.86, 2 ,241.86, 2 , 0 , 0 , 0 ,0,
       1       1
      -3   19.81
       1       1
      -3   19.81
Pier Skew, UpSta & Num, DnSta & Num=  ,254.85, 2 ,256.85, 2 , 0 , 0 , 0 ,0,
       1       1
      -3   19.81
       1       1
      -3   19.81
Pier Skew, UpSta & Num, DnSta & Num=  ,269.8, 2 ,271.8, 2 , 0 , 0 , 0 ,0,
       1       1
      -3   19.81
       1       1
      -3   19.81
Pier Skew, UpSta & Num, DnSta & Num=  ,284.76, 2 ,286.76, 2 , 0 , 0 , 0 ,0,
       1       1
      -3   19.81
       1       1
      -3   19.81
Pier Skew, UpSta & Num, DnSta & Num=  ,299.77, 2 ,301.77, 2 , 0 , 0 , 0 ,0,
       1       1
      -3   19.81
       1       1
      -3   19.81
Pier Skew, UpSta & Num, DnSta & Num=  ,314.06, 2 ,316.06, 2 , 0 , 0 , 0 ,0,
       1       1
      -3   19.81
       1       1
      -3   19.81
BR Coef=-1 , 1 , 1 ,0.9, 0 ,,,0.8,-1,1.2,1,
WSPro=,,,, 1 ,,,, 0 ,,,, 0 ,,,,-1 ,-1 ,-1 , 0 , 0 , 0 , 0 , 0
BC Design=,, 0 ,, 0 ,,,,,,
BC HTab HWMax=18.82
BC Use User HTab Curves=0
BC User HTab FreeFlow(D)= 0

Type RM Length L Ch R = 1 ,1427.06 ,56.76,61.93,60.54
BEGIN DESCRIPTION:
Copy of 435s10u.  XS 2/4.  Adjust elevations as needed.
Bank Station offset =      4743
Ineffective flow on ROB stationed based on high ground in XS 2/4.
END DESCRIPTION:
XS GIS Cut Line= 6
     3260178.218    13861332.302      3260106.16    13861157.913
     3260083.385    13861105.818     3260046.567    13861034.414
     3259968.469    13860840.285     3259934.999    13860767.766
#Sta/Elev= 30
       0   19.51   55.87   18.82  107.31   16.98  146.24   13.65  213.07    8.73
  235.55    7.43  245.94    2.79  247.53    1.36  248.88    -.05  257.25   -1.69
  257.54    1.35  259.07    3.44  263.39    5.02  285.21       8  309.22   11.91
  348.38   13.68   403.2    15.7  416.75   11.54  425.07   12.28  441.58   13.12
  465.09   14.24  505.84   15.23  519.47   15.56  535.13   16.26  540.57   16.48
   553.4   17.72  568.69   19.43  589.24   20.33  608.85   20.39     615   20.41
#Mann= 3 ,-1 , 0
       0     .13       0  146.24     .04       0  348.38     .13       0
#XS Ineff= 2 , 0
       0   55.87   22.05   403.2       0   22.05
Permanent Ineff=
       F       F
Bank Sta=235.55,263.39
XS Rating Curve= 0 ,0
Exp/Cntr=0.5,0.3

Type RM Length L Ch R = 1 ,1365.134,714.53,746.5,753.25
BEGIN DESCRIPTION:
Copy of 435s10u.  XS 1/4.  Adjust elevations as needed.
Bank Station offset =      4708
END DESCRIPTION:
XS GIS Cut Line= 4
     3260212.804    13861316.682     3260139.169    13861099.124
     3260045.452    13860891.607     3259942.809    13860674.048
#Sta/Elev= 27
       0   19.16   25.82   18.38   91.12   18.82  142.56   16.98  181.49   13.65
  248.32    8.73   270.8    7.43  281.19    2.79  282.78    1.36  284.13    -.05
   292.5   -1.69  292.79    1.35  294.32    3.44  298.64    5.02  320.46       8
  344.47   11.91  383.63   13.68  438.45    15.7  449.46   15.83  498.06   17.71
  511.18   17.34  539.96   18.05   562.2   19.55  591.98   20.09  595.47   20.25
   680.5   21.05  697.94   21.07
#Mann= 3 , 0 , 0
       0     .13       0   270.8     .04       0  298.64     .13       0
Bank Sta=270.8,298.64
XS Rating Curve= 0 ,0
Exp/Cntr=0.3,0.1

Type RM Length L Ch R = 1 ,618.632 ,54.73,51.12,46.55
BEGIN DESCRIPTION:
435s11u.  XS 4/4.
Bank Station offset =      4570
END DESCRIPTION:
XS GIS Cut Line= 6
     3260642.486    13861062.573     3260724.903    13860631.652
     3260705.317    13860468.548     3260605.874    13860307.685
     3260281.223    13860064.927     3259883.452    13859974.259
#Sta/Elev= 30
       0   16.36   95.04   15.56  177.01   13.37  277.52    5.75  285.16    4.83
  315.66    4.11  348.29    5.73  374.66    5.45  407.83     4.1  408.61    1.79
  410.68   -1.01  430.34   -2.45  433.27    1.81  434.84    4.81  462.15    5.12
  507.33    7.13  526.24    8.92  547.61    9.85   576.7   13.85     606   15.14
   841.6   16.52  992.75   18.29  1005.8   18.32  1055.9   16.75 1145.12   18.69
  1160.1   18.28 1237.02   19.86 1361.02   20.75 1420.48   22.81 1605.63   24.31
#Mann= 3 , 0 , 0
       0      .1       0  407.83     .04       0  434.84     .12       0
Bank Sta=407.83,434.84
XS Rating Curve= 0 ,0
Exp/Cntr=0.5,0.3

Type RM Length L Ch R = 1 ,567.508 ,25.31,24.78,23.67
BEGIN DESCRIPTION:
Copy of 435s11u.  XS 3/4.  No elevation adjustment required.
Bank Station offset =      4567
Manning's 'n' value increased here to represent increase
roughness thru the bridge -- mbb
END DESCRIPTION:
XS GIS Cut Line= 6
     3260761.855    13861073.461     3260776.493    13860929.744
      3260771.17    13860663.603     3260748.548    13860430.729
     3260550.709    13860050.615     3259975.898     13859422.67
#Sta/Elev= 30
       0   16.03  144.39   14.75     155   13.67  296.01    7.11  309.54    5.92
  376.83    5.45     410     4.1  410.78    1.79  412.85   -1.01  432.51   -2.45
  437.01    4.81  451.33    4.73  553.88    9.87  595.24   10.41  640.93   13.84
  659.73   14.42  725.02   13.98  826.53   15.92  867.36   15.03   941.8   16.92
  967.42   15.75    1021   16.83 1056.17   15.97 1223.81   16.53 1284.07   15.52
 1523.17   18.17 1579.89   19.38  1709.9   24.24 1894.88   25.21  1924.9   24.17
#Mann= 3 ,-1 , 0
       0      .1       0  376.83     .04       0  451.33     .12       0
#XS Ineff= 2 , 0
       0     395    7.13     463       0    7.13
Permanent Ineff=
       F       F
Bank Sta=410,437.01
XS Rating Curve= 0 ,0
Exp/Cntr=0.5,0.3

Type RM Length L Ch R = 3 ,555.119 ,,,
BEGIN DESCRIPTION:
435s11- Private Drive
Shift the centerline: -3ft
END DESCRIPTION:
Bridge Culvert--1,0,-1,-1, 0
Deck Dist Width WeirC Skew NumUp NumDn MinLoCord MaxHiCord MaxSubmerge Is_Ogee
6,12,2.6,0, 8, 8, , , 0.95, 0, 0,0,,
       0  350.86  373.51  403.14  457.62  479.61   524.6    1000
    7.13    7.13    7.14     7.4    7.38    7.98    9.87    9.87
               0       0    6.16    6.16       0       0
       0  348.86  371.51  401.14  455.62  477.61   522.6    1000
    7.13    7.13    7.14     7.4    7.38    7.98    9.87    9.87
               0       0    6.16    6.16       0       0
Pier Skew, UpSta & Num, DnSta & Num=  ,424.59, 2 ,422.59, 2 , 0 , 0 , 0 ,0,
       1       1
      -2     6.3
       1       1
      -2     6.3
Pier Skew, UpSta & Num, DnSta & Num=  ,442.99, 2 ,440.99, 2 , 0 , 0 , 0 ,0,
       1       1
      -2     6.3
       1       1
      -2     6.3
BR Coef=-1 , 0 , 0 ,, 0 ,,,0.8,0,,1,
WSPro=,,,, 1 ,,,, 0 ,,,, 0 ,,,,-1 ,-1 ,-1 , 0 , 0 , 0 , 0 , 0
BC Design=,, 0 ,, 0 ,,,,,,
BC HTab HWMax=25.21
BC Use User HTab Curves=0
BC User HTab FreeFlow(D)= 0

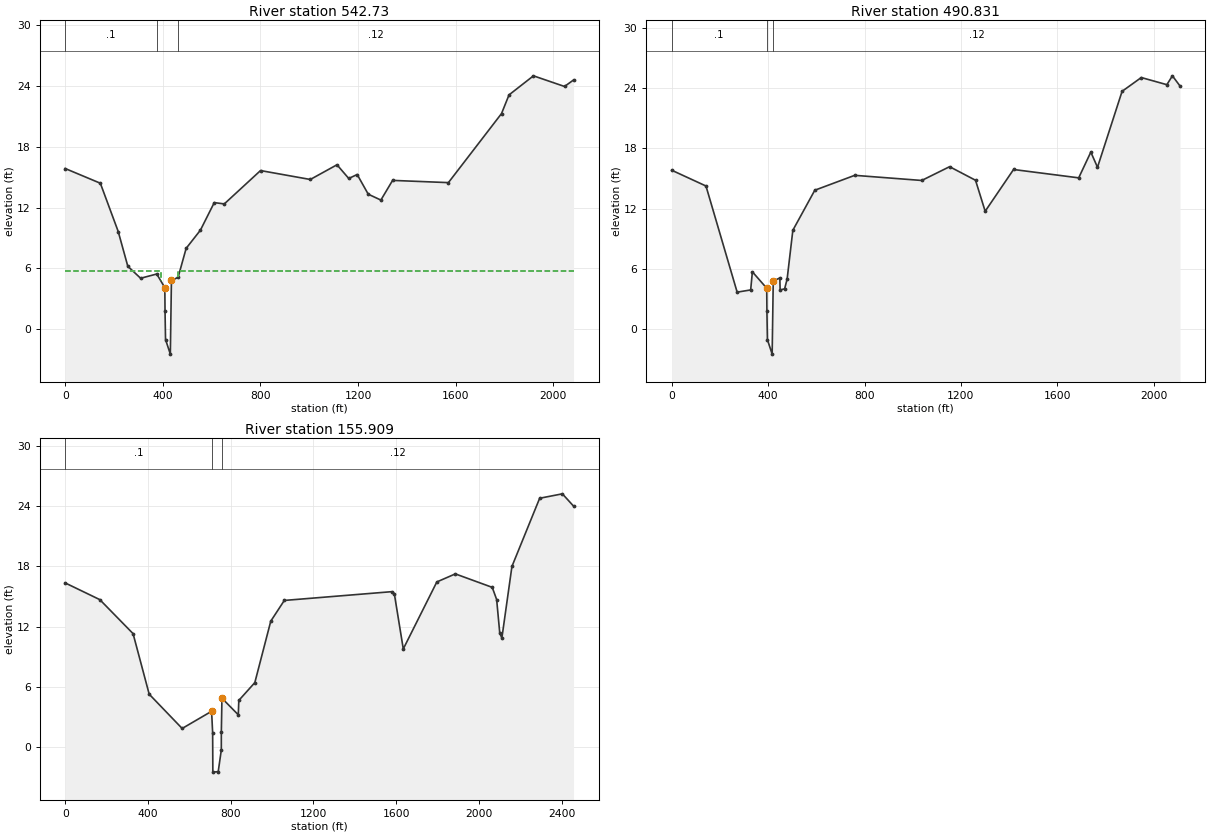
Type RM Length L Ch R = 1 ,542.73  ,38.47,51.9,62.21
BEGIN DESCRIPTION:
Copy of 435s11u.  XS 2/4.  No elevation adjustment required.
Bank Station offset =      4569
Manning's 'n' value increased here to represent increase
roughness thru the bridge -- mbb
END DESCRIPTION:
XS GIS Cut Line= 6
     3260811.091    13861073.461     3260792.461    13860578.438
     3260776.493    13860402.784     3260676.816    13860079.434
      3260470.63    13859762.726      3260070.09    13859195.644
#Sta/Elev= 30
       0   15.85  143.93    14.4  217.16    9.64  256.51    6.21  308.97    5.03
  375.01    5.45  408.18     4.1  408.96    1.79  411.03   -1.01  430.69   -2.45
  435.19    4.81   462.5    5.12  495.46    7.98  553.85    9.77  610.63   12.49
  651.76   12.36  800.18   15.65 1004.14   14.77 1113.46   16.22  1161.6   14.87
 1196.17   15.26 1241.47   13.32 1293.23   12.74 1341.27   14.68  1569.9   14.46
 1787.56   21.27 1818.24   23.11 1918.31   24.99 2045.63   23.94 2082.53   24.58
#Mann= 3 ,-1 , 0
       0      .1       0  375.01    .045       0   462.5     .12       0
#XS Ineff= 2 , 0
       0     393    5.75     462       0    5.75
Permanent Ineff=
       F       F
Bank Sta=408.18,435.19
XS Rating Curve= 0 ,0
Exp/Cntr=0.5,0.3

Type RM Length L Ch R = 1 ,490.831 ,286.15,334.92,318.92
BEGIN DESCRIPTION:
Copy of 435s11u.  XS 1/4.  No elevation adjustment required.
Bank Station offset =      4583
END DESCRIPTION:
XS GIS Cut Line= 6
     3260843.028    13861082.776     3260830.056    13860697.271
     3260852.898    13860639.407     3260823.312    13860294.596
     3260585.302    13859854.762     3260120.808    13859185.983
#Sta/Elev= 30
       0   15.83  142.29   14.26  271.61    3.71  327.72    3.93  334.81    5.73
  394.35     4.1  395.13    1.79   397.2   -1.01  416.86   -2.45  421.36    4.81
  448.67    5.12   449.9    3.93  468.59    4.04  478.92       5   502.7    9.86
  593.76   13.84  759.32   15.32 1037.42   14.81 1152.98   16.18 1260.55   14.83
 1300.56   11.75  1418.3    15.9 1688.58   15.07 1738.87   17.63 1766.53   16.12
 1868.56   23.67  1948.2   25.04 2054.29   24.33  2077.3   25.21  2108.8    24.2
#Mann= 3 , 0 , 0
       0      .1       0  394.35    .045       0  421.36     .12       0
Bank Sta=394.35,421.36
XS Rating Curve= 0 ,0
Exp/Cntr=0.3,0.1

Type RM Length L Ch R = 1 ,155.909 ,462.11,155.91,382.32
BEGIN DESCRIPTION:
435v11
Bank Station offset =      4260
Overbank reachlengths > channel distance since this is the most downstream cross section.
END DESCRIPTION:
XS GIS Cut Line= 5
     3260892.503    13861261.164     3261162.483    13860658.884
     3261097.238    13860491.946     3260892.503      13860097.1
     3260171.527    13859171.492
#Sta/Elev= 30
       0   16.35  167.26   14.69  328.06   11.31  405.99    5.29  565.33    1.88
   707.7    3.59   712.7    1.46   713.7   -2.46   739.7   -2.41   754.7    -.25
   754.7    1.48   757.7    4.89   836.7    3.24  839.26    4.67  916.62    6.44
  993.73   12.55 1059.15   14.61 1577.56   15.48 1590.89   15.29 1634.27    9.79
 1796.52   16.45 1885.93   17.25 2064.35   15.91 2085.63    14.7 2100.65   11.37
 2110.84   10.87 2159.51   17.99 2293.56   24.77 2403.29   25.21 2457.29   23.99
#Mann= 3 , 0 , 0
       0      .1       0   707.7     .04       0   757.7     .12       0
Bank Sta=707.7,757.7
XS Rating Curve= 0 ,0
Exp/Cntr=0.3,0.1

Chan Stop Cuts=-1
Use User Specified Reach Order=0
Composite Channel Slope=5